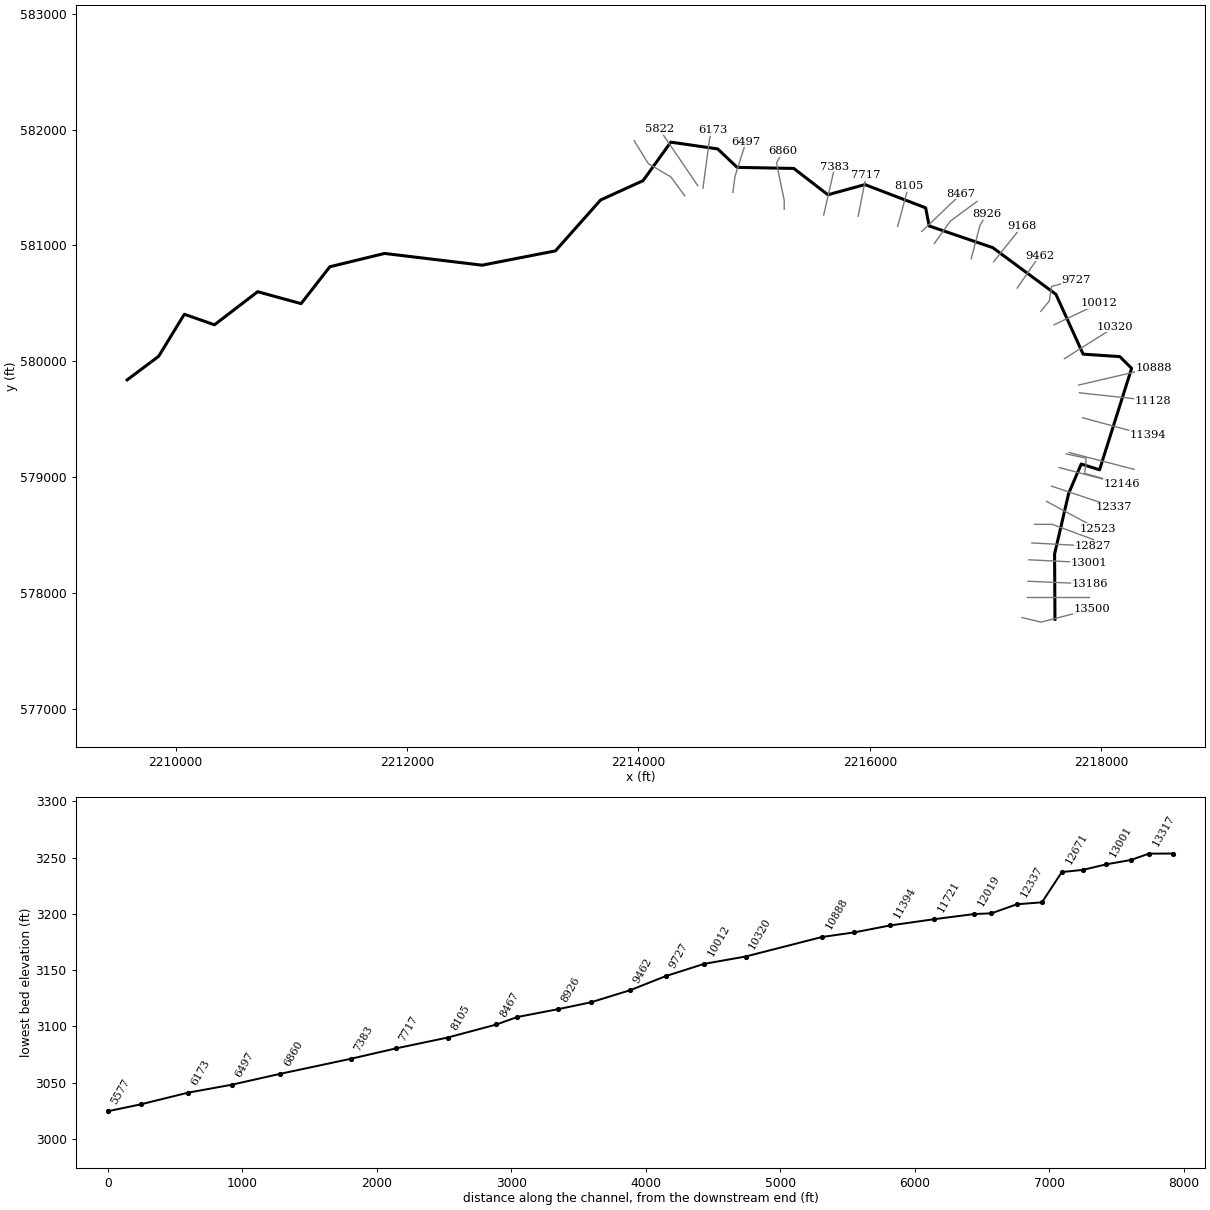
--- COALBNKFK.prj (project) ---

Proj Title=COALBNKFK
Current Plan=p01
Default Exp/Contr=0,0
English Units
Geom File=g01
Flow File=f01
Plan File=p01
BEGIN DESCRIPTION:
----------MODEL BY WOOD PLC 2022----------
AFH study
Randolph County, WV
HEC-RAS Version: RAS 6.2
Vertical Datum: NAVD88
Projection: NAD 1983 StatePlane West Virginia S FIPS 4702 (US Feet)
Terrain: 1-meter LIDAR (FEMA Region III 3DEP collected 2016-2018)
Land Use: 2019 NLCD
Hydrologic Method:
WV SIR2010-5033 regression equations
Additional Model Notes:
KWSEL tie-in with BFKELKRV due to coincident peak
Mapping to correct backwater from RS 12000 - RS 12600 using BFE
END DESCRIPTION:
DSS Export Rating Curves= 0
DSS Export Rating Curve Sorted= 0
DSS Export Volume Flow Curves= 0
DXF OffsetX= 0
DXF OffsetY= 0
DXF ScaleX= 0
DXF ScaleY= 0

--- COALBNKFK.p01 (plan) ---

Plan Title=Floodplain
Program Version=6.20
Short Identifier=Floodplain
Geom File=g01
Flow File=f01
Subcritical Flow
K Sum by GR= 0
Std Step Tol= 0.01
Critical Tol= 0.01
Num of Std Step Trials= 20
Max Error Tol= 0.3
Flow Tol Ratio= 0.001
Split Flow NTrial= 30
Split Flow Tol= 0.02
Split Flow Ratio= 0.02
Log Output Level= 0
Friction Slope Method= 1
Unsteady Friction Slope Method= 2
Unsteady Bridges Friction Slope Method= 1
Parabolic Critical Depth
Global Vel Dist= 0 , 0 , 0
Global Log Level= 0
CheckData=True
Encroach Param=-1 ,0,0, 0
Mapping Interval=1HOUR
Computation Time Step Use Courant=        0
Computation Time Step Use Time Series=    0
Computation Time Step Count To Double=0
Computation Time Step Max Doubling=0
Computation Time Step Max Halving=0
Computation Time Step Residence Courant=0
Run HTab= 0
Run UNet= 0
Run Sediment= 0
Run PostProcess= 0
Run WQNet= 0
Run RASMapper=-1
UNET Theta= 0
UNET Theta Warmup= 0
UNET ZTol= 0
UNET ZSATol= 0
UNET MxIter= 0
UNET Max Iter WO Improvement= 0
UNET MaxInSteps= 0
UNET DtIC= 0
UNET DtMin= 0
UNET MaxCRTS= 0
UNET WFStab= 0
UNET SFStab= 0
UNET WFX= 1
UNET SFX= 1
UNET Gravity=32.174
UNET 1D Methodology=Finite Difference
UNET DSS MLevel= 1
UNET Pardiso=0
UNET DZMax Abort= 0
UNET Use Existing IB Tables= 0
UNET Froude Reduction=False
UNET Froude Limit= 0
UNET Froude Power= 0
UNET D1 Cores= 0
UNET WindReference=Eulerian
UNET WindDragFormulation=Hsu (1988)
UNET D2 Coriolis=0
UNET D2 Cores= 0
UNET D2 Theta= 1
UNET D2 Theta Warmup= 1
UNET D2 Z Tol= 0.01
UNET D2 Volume Tol= 0.01
UNET D2 Max Iterations= 20
UNET D2 Equation= 0
UNET D2 RampUpFraction=0.1
UNET D2 TimeSlices= 1
UNET D2 Turbulence Formulation=Non-Conservative (original)
UNET D2 Eddy Viscosity=0.3
UNET D2 Transverse Eddy Viscosity=0.1
UNET D2 Smagorinsky Mixing=0
UNET D2 BCVolumeCheck=0
UNET D2 Cores=0
UNET D2 SolverType=PARDISO (Direct)
UNET D2 Minimum Iterations= 2147483647
UNET D2 Maximum Iterations= 2147483647
UNET D2 Restart Number= 10
UNET D2 Relaxation Coeff=1.3
UNET D2 SOR Precondition Iterations= 10
UNET D2 ILUT Maximum Fill= 8
UNET D2 ILUT Tolerance=1E-08
UNET D1D2 MaxIter= 0
UNET D1D2 ZTol=0.01
UNET D1D2 QTol=0.1
UNET D1D2 MinQTol=1
Write IC File= 0
Write IC File at Fixed DateTime=0
Write IC File at Sim End=0
Echo Input=False
Echo Parameters=False
Echo Output=False
Write Detailed= 0
HDF Write Warmup=0
HDF Write Time Slices=0
HDF Flush=0
HDF Compression= 1
HDF Chunk Size= 1
HDF Spatial Parts= 1
HDF Use Max Rows=0
HDF Fixed Rows= 1
Calibration Method= 0
Calibration Iterations= 20
Calibration Max Change=0.05
Calibration Tolerance=0.2
Calibration Maximum=1.5
Calibration Minimum=0.5
Calibration Optimization Method= 1
WQ AD Non Conservative
WQ ULTIMATE=-1
WQ Max Comp Step=1HOUR
WQ Output Interval=15MIN
WQ Output Selected Increments= 0
WQ Output face flow=0
WQ Output face velocity=0
WQ Output face area=0
WQ Output face dispersion=0
WQ Output cell volume=0
WQ Output cell surface area=0
WQ Output cell continuity=0
WQ Output cumulative cell continuity=0
WQ Output face conc=0
WQ Output face dconc_dx=0
WQ Output face courant=0
WQ Output face peclet=0
WQ Output face adv mass=0
WQ Output face disp mass=0
WQ Output cell mass=0
WQ Output cell source sink temp=0
WQ Output nsm pathways=0
WQ Output nsm derived pathways=0
WQ Create Restart=0
WQ Fixed Restart=0
WQ System Summary=0
WQ Write To DSS=0
Sorting and Armoring Iterations= 10
XS Update Threshold= 0.02
Bed Roughness Predictor= 0
Hydraulics Update Threshold= 0.02
Energy Slope Method= 1
Volume Change Method= 1
Sediment Retention Method= 0
Sediment TS Multiplier= 1
Warm Up Method= 0
XS Weighting Method= 0
Number of US Weighted Cross Sections= 1
Number of DS Weighted Cross Sections= 1
Upstream XS Weight=0
Main XS Weight=1
Downstream XS Weight=0
Number of DS XS's Weighted with US Boundary= 1
Upstream Boundary Weight= 1
Weight of XSs Associated with US Boundary= 0
Number of US XS's Weighted with DS Boundary= 1
Downstream Boundary Weight= 0.5
Weight of XSs Associated with DS Boundary= 0.5
Percentile Method= 0
Sediment Output Level= 3
Mass or Volume Output= 0
Output Increment Type= 1
Profile and TS Output Increment= 1
Transport Output Increment 1
XS Output Flag= 0
XS Output Increment= 10
Read HDF5 Sediment Hotstart= 0
Sediment Hotstart Type= 0
Write Gradation File= 0
Read Gradation Hotstart= 0
Write HDF5 File= 1
Write Binary Output= 1
Write DSS Sediment File= 0
DSS Sediment Output Type= 1
SV Curve= 0
Specific Gage Flag= 0
Subcell Erosion Methods= 0
Subcell Deposition Methods= 0
Advection Scheme= 1
Matrix Solver= 0
Implicit Weighting Factor= 1
Maximum Outer Loop Convergence Iterations= 5
Convergence Maximum Absolute= 0.001
Convergence RMSE= 0.0001
Grain Fractions Max Abs Error= 0.001
Max Subgrid Regions= 1
Max Subgrid Length Scale= 3.402823E+38
Initial Layer Thickness= 3.402823E+38
Min Layer Thickness= 3.402823E+38
Max Layer Thickness= 3.402823E+38
Number of Layers= 5

--- COALBNKFK.f01 (steady flow) ---

Flow Title=Flow
Program Version=6.20
Number of Profiles= 1
Profile Names=P100yr
River Rch & RM=COALBNKFK,Main            ,13500
     479
River Rch & RM=COALBNKFK,Main            ,9462
     604
River Rch & RM=COALBNKFK,Main            ,8926
     674
River Rch & RM=COALBNKFK,Main            ,6497
     753
River Rch & RM=COALBNKFK,Main            ,4497
     858
River Rch & RM=COALBNKFK,Main            ,0
    2210
Boundary for River Rch & Prof#=COALBNKFK,Main            , 1
Up Type= 0
Dn Type= 1
Dn Known WS=2859.8
DSS Import GetInterval= 0
DSS Import GetPeak= 0
DSS Import FillOption= 0

--- COALBNKFK.g01 (geometry) ---

Geom Title=Geometry
Program Version=6.20

River Reach=COALBNKFK       ,Main
Reach XY= 30
2217599.87300001577771.7150000182217596.65600003578335.523000002
     2217718.832578860.3870000092217826.90400003579112.557000011
2217985.25200003579062.5999999942218262.46800001 579938.92900002
2218160.59900001580040.0310000182217843.46400003580061.298000008
2217608.04700001580577.9650000042217062.23000003580980.996999994
2216512.54399998581168.302000016     2216482.381581324.715000004
     2215957.296581525.5479999932215637.20400003581437.717000008
2215342.32300001 581664.990000012214852.51100004581674.308000013
2214684.91900001581833.4989999982214279.29599999581892.107000008
2214039.39400002581559.5310000032213672.36500002581392.465000018
2213282.16200002580953.2040000112212648.01300001580829.578999996
2211805.16800001 580930.946000012211331.75300004580815.893000022
2211083.62600003580497.516000018     2210708.153580600.476000011
2210334.74599999580314.8680000012210074.31800003580405.863000005
     2209852.153580042.4070000052209579.97135524579839.093552318

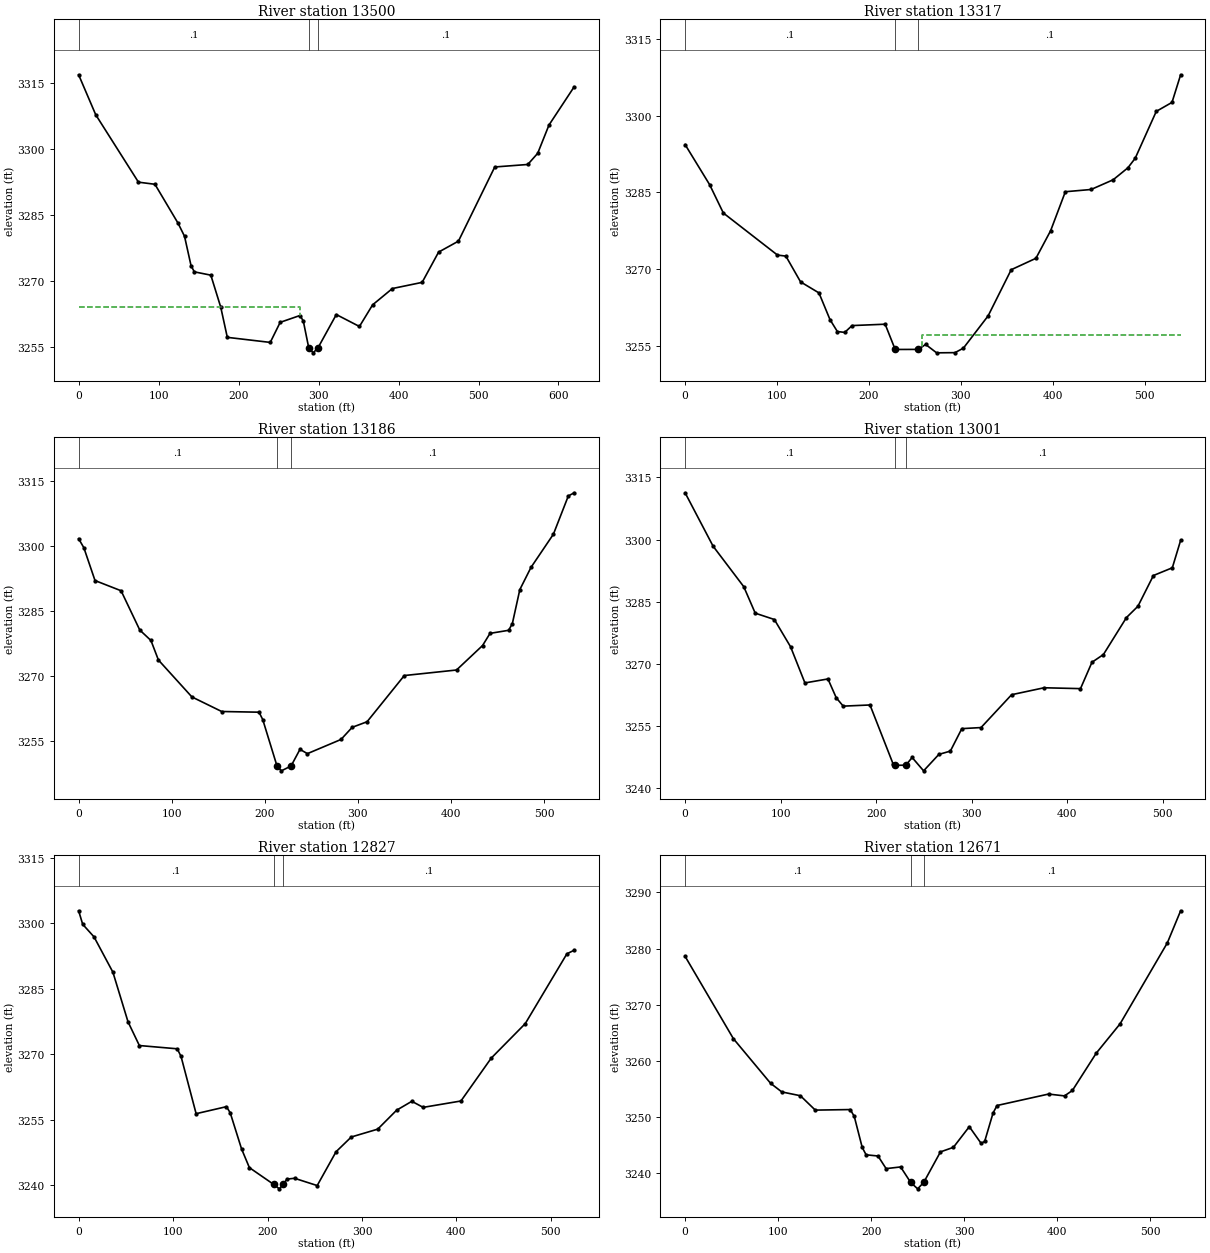
Type RM Length L Ch R = 1 ,13500   ,184.4,183.5,181.7
XS GIS Cut Line= 3
2217315.40184916577786.6589374932217479.29341297577747.579437755
2217916.34400876577859.293424582
#Sta/Elev= 30
       0 3316.87    21.4 3307.78    74.8 3292.47    95.4 3291.99   124.2 3283.18
   132.4 3280.18   140.6 3273.46   144.7 3272.09   165.3 3271.34   177.7 3264.06
   185.9 3257.21   239.6 3256.06     252 3260.62   276.7 3262.17   280.9 3260.94
   287.73254.842   293.3 3253.69  299.32 3254.84   322.2 3262.39   351.1 3259.68
   367.6  3264.6   392.3  3268.3   429.5  3269.7   450.1 3276.58   474.9 3279.07
   520.3 3295.92   561.6 3296.49     574 3299.03   588.1 3305.45   619.6 3314.14
#Mann= 3 ,-1,0
       0      .1       0   287.7    .045       0  299.32      .1       0
#XS Ineff= 2 , 0
           276.7    3264
Permanent Ineff=
       F       F
Bank Sta=287.7,299.32
XS Rating Curve= 0 ,0
Exp/Cntr=0.3,0.1

Type RM Length L Ch R = 1 ,13317   ,131.4,131.1,132
XS GIS Cut Line= 2
2217358.56643211577960.1021971492217897.52178412577960.102197149
#Sta/Elev= 30
       0 3294.37    26.7 3286.51    41.6 3280.96   100.5 3272.72   109.6 3272.52
   125.6 3267.47   145.6 3265.31   157.6 3260.08   165.6 3257.75   173.6 3257.57
   181.6 3258.91   217.6 3259.18   228.5 3254.23  253.823254.244   261.6 3255.22
   273.6 3253.57   293.6 3253.61   302.7 3254.49   329.6 3260.81   354.7 3269.85
   381.6 3272.09   397.6  3277.5   413.6 3285.13   441.6 3285.57   465.6 3287.47
   481.6 3289.81   489.6 3291.69   512.5 3300.87   529.6 3302.63     539 3308.04
#Mann= 3 ,-1,0
       0      .1       0   228.5    .045       0  253.82      .1       0
#XS Ineff= 2 , 0
                           257.6            3257
Permanent Ineff=
       F       F
Bank Sta=228.5,253.82
XS Rating Curve= 0 ,0
Exp/Cntr(USF)=0,0
Exp/Cntr=0.3,0.1

Type RM Length L Ch R = 1 ,13186   ,184.7,184.7,184.6
XS GIS Cut Line= 2
2217366.58709634578100.4450084992217898.51877761578077.271747137
#Sta/Elev= 30
       0 3301.72     5.6 3299.64    17.6 3292.04    45.6 3289.68    65.7 3280.59
    77.7 3278.17    85.7 3273.66   121.7 3265.11   153.7 3261.74   193.8 3261.58
   197.8 3259.88  213.133249.128   217.8 3248.01  228.243249.128   237.8 3252.98
   245.8 3251.99   281.9 3255.27   293.9 3258.08   309.9 3259.37   349.9 3270.06
     406 3271.34     434 3277.01     442 3279.82     462 3280.53     466  3282.1
     474 3289.94     486 3295.08   510.1 3302.77   526.1 3311.61   532.4 3312.35
#Mann= 3 ,-1,0
       0      .1       0  213.13    .045       0  228.24      .1       0
Bank Sta=213.13,228.24
XS Rating Curve= 0 ,0
Exp/Cntr(USF)=0,0
Exp/Cntr=0.3,0.1

Type RM Length L Ch R = 1 ,13001   ,171.9,173.6,171.1
XS GIS Cut Line= 2
2217374.88666978578285.7062105492217892.89093014578259.996440274
#Sta/Elev= 30
       0  3311.3    29.3 3298.39    61.4  3288.6    73.4  3282.2    93.4 3280.67
   110.4 3274.07   125.4 3265.34   149.5  3266.3   158.2 3261.74   165.5 3259.73
   193.5 3260.01   217.6 3245.81   219.9 3245.42  231.07 3245.46   237.6 3247.32
   249.6 3244.09   265.6 3248.07   277.6 3248.86   289.6 3254.29   309.7 3254.55
   341.7 3262.49   375.7 3264.17   413.8 3263.96   425.8 3270.33   437.8 3272.21
   461.9 3281.14   473.9 3283.87   490.1  3291.3   509.9 3293.17   518.6  3299.8
#Mann= 3 ,-1,0
       0      .1       0   219.9    .045       0  231.07      .1       0
Bank Sta=219.9,231.07
XS Rating Curve= 0 ,0
Exp/Cntr(USF)=0,0
Exp/Cntr=0.3,0.1

Type RM Length L Ch R = 1 ,12827   ,158,156.8,155.2
XS GIS Cut Line= 2
2217399.93086517578431.2075976162217923.92098913578403.096947307
#Sta/Elev= 30
       0 3302.89     4.3 3299.79    16.3 3296.91    36.3 3288.81    52.3 3277.44
    64.3 3272.01   104.4 3271.26   108.4 3269.54   124.4 3256.39   156.5    3258
   160.5  3256.6   172.5 3248.33   180.8 3244.03  206.65 3240.17   212.5 3239.17
   216.6 3240.19   220.6  3241.4   228.6 3241.59   252.6 3239.92   272.6 3247.68
   288.7 3251.05   316.7 3252.85   336.7 3257.19   352.8 3259.23   364.8 3257.84
   404.8  3259.3   436.9 3269.13   472.9 3277.03     517 3293.03   524.7 3293.85
#Mann= 3 ,-1,0
       0      .1       0  206.65    .045       0   216.6      .1       0
Bank Sta=206.65,216.6
XS Rating Curve= 0 ,0
Exp/Cntr=0.3,0.1

Type RM Length L Ch R = 1 ,12671   ,148.8,147.9,145.5
XS GIS Cut Line= 3
2217424.24487327578592.2618684322217576.85230269578591.295998626
2217933.25826128578459.937704946
#Sta/Elev= 30
       0 3278.62    51.9 3263.96    91.9 3256.01   103.9 3254.48   123.9  3253.8
   139.9 3251.24   177.5 3251.34   181.8 3250.11   190.3 3244.61   194.5 3243.28
   207.3 3243.07     216 3240.82   231.6 3241.12   242.4 3238.36   249.9 3237.22
  256.45 3238.37   274.4  3243.8   288.3 3244.61   305.4 3248.29   318.1 3245.32
   321.9 3245.66   330.9 3250.71   335.2 3252.06   390.6  3254.1   407.7 3253.77
   416.2 3254.74   441.8 3261.38   467.4  3266.6   518.2 3281.02   532.5 3286.74
#Mann= 3 ,-1,0
       0      .1       0   242.4    .045       0  256.45      .1       0
Bank Sta=242.4,256.45
XS Rating Curve= 0 ,0
Exp/Cntr(USF)=0,0
Exp/Cntr=0.3,0.1

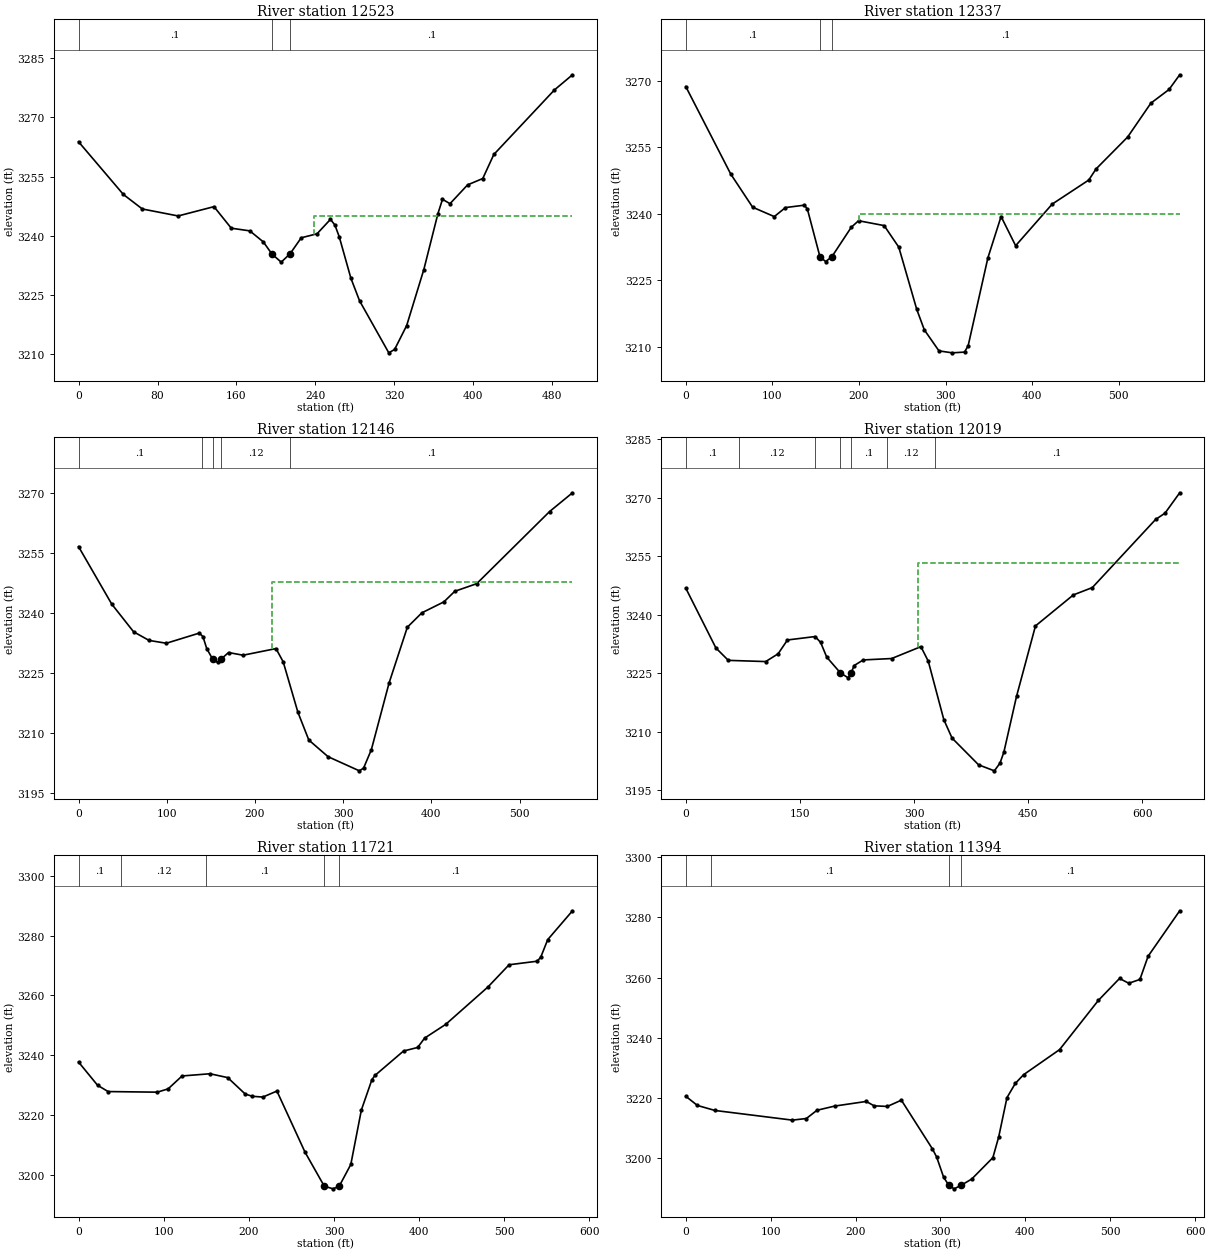
Type RM Length L Ch R = 1 ,12523   ,183.1,186.1,187.5
XS GIS Cut Line= 2
2217527.22050567578789.6917778952217968.28123449578553.375500526
#Sta/Elev= 30
       0 3263.81    45.4 3250.46    64.6 3246.78   100.9 3245.01   137.2 3247.37
   154.7 3241.91   173.5 3241.23   187.2 3238.43   195.9 3235.37   205.3  3233.3
   214.4 3235.46   225.6 3239.48   241.6 3240.49   255.2 3244.15   259.7 3242.71
   264.1 3239.73   275.9 3229.23   284.7  3223.5   314.3 3210.32   320.2 3211.18
   332.4 3217.23   349.8 3231.44   364.1 3245.63   368.7 3249.23   376.3 3248.12
   394.1 3252.88   409.5  3254.5   420.7 3260.59   482.1 3276.95   500.4 3280.79
#Mann= 3 ,-1,0
       0      .1       0   195.9    .045       0   214.4      .1       0
#XS Ineff= 2 , 0
                        238.3623            3245
Permanent Ineff=
       F       T
Bank Sta=195.9,214.4
XS Rating Curve= 0 ,0
Exp/Cntr=0.3,0.1

Type RM Length L Ch R = 1 ,12337   ,189.9,190.7,190
XS GIS Cut Line= 2
2217570.96120256578921.3358285522218111.84829418578740.718174742
#Sta/Elev= 30
       0 3268.72    51.9 3248.97    77.2 3241.48   102.2 3239.36   115.1  3241.4
     137 3241.94   140.4 3241.06  154.91 3230.29   161.5 3229.21   168.6 3230.29
   191.1 3236.96   199.5 3238.43     229 3237.33   245.9 3232.47   266.6 3218.45
   275.4 3213.79   292.3 3209.05   307.7 3208.61   321.8 3208.78     326 3210.22
   348.8 3230.07     364 3239.38   380.8 3232.79     423 3242.18   465.2 3247.61
   473.6 3250.11   510.1 3257.32   536.9 3264.96   557.9 3268.05   570.2 3271.37
#Mann= 3 ,-1,0
       0      .1       0  154.91    .045       0   168.6      .1       0
#XS Ineff= 2 , 0
                           199.5            3240
Permanent Ineff=
       F       T
Bank Sta=154.91,168.6
XS Rating Curve= 0 ,0
Exp/Cntr(USF)=0,0
Exp/Cntr=0.3,0.1

Type RM Length L Ch R = 1 ,12146   ,135.1,126.9,118.7
XS GIS Cut Line= 2
2217635.80456688579082.3887854652218177.15828555578939.563549049
#Sta/Elev= 30
       0 3256.57    37.6 3242.21    62.4 3235.28    79.9 3233.13    99.5 3232.42
   136.9 3234.96     141 3234.08   145.3 3231.09   151.9 3228.49   157.6 3227.63
   161.7 3228.47   161.7 3228.48     170  3230.1   186.5 3229.43   223.8 3231.09
     232 3227.76   248.6  3215.2     261 3208.23   282.8 3204.07   318.3 3200.53
   323.1 3201.22   331.9 3205.82     352  3222.5   372.7 3236.43   389.2 3240.03
   414.1 3242.76   426.5 3245.41   451.3 3247.31     534 3265.35   559.9 3270.03
#Mann= 5 ,-1,0
       0      .1       0     140     .12       0   151.9    .045       0
   161.7     .12       0     240      .1       0
#XS Ineff= 2 , 0
                          219.79         3247.84
Permanent Ineff=
       F       F
Bank Sta=151.9,161.7
XS Rating Curve= 0 ,0
Exp/Cntr(USF)=0,0
Exp/Cntr=0.3,0.1

Type RM Length L Ch R = 1 ,12019   ,286.4,298.3,309.8
XS GIS Cut Line= 5
2217697.42078079579199.6503819122217868.14322558579163.934534916
2217867.94733328579103.5924974352217853.52908547579032.611496408
2218182.68751495578940.999420573
#Sta/Elev= 30
       0 3246.79    39.6 3231.44    55.9 3228.26     105 3227.95   121.3 3229.94
   133.6 3233.49     170 3234.37   177.2 3232.85   185.2 3229.09  203.15 3225.05
   213.2  3223.8   217.3 3225.06   221.2 3226.93   233.2 3228.37   270.5 3228.73
   308.9 3231.78   318.6 3228.04     339 3213.06   349.8 3208.33   384.7 3201.46
   405.4 3199.92   412.8 3201.89   417.9 3204.72   434.5    3219   459.4 3237.09
   509.2 3245.05   534.1 3246.93   617.2  3264.4   629.6 3266.02   648.9 3271.25
#Mann= 7 ,-1,0
       0      .1       0      70     .12       0     170      .1       0
  203.15    .045       0   217.3      .1       0  264.76     .12       0
  327.19      .1       0
#XS Ineff= 2 , 0
                          305.24          3253.2
Permanent Ineff=
       F       F
Bank Sta=203.15,217.3
XS Rating Curve= 0 ,0
Exp/Cntr(USF)=0,0
Exp/Cntr=0.3,0.1

Type RM Length L Ch R = 1 ,11721   ,325.8,326.4,324.9
XS GIS Cut Line= 2
2217722.57590776579211.7092771572218284.35194078579066.583801959
#Sta/Elev= 30
       0 3237.74    22.3 3229.98    34.7 3227.86    92.5 3227.66   105.2 3228.76
   121.6 3233.08   154.4 3233.82   175.2 3232.53   195.8 3227.03   204.1 3226.28
   216.5 3226.02     233 3228.03     266  3207.6  288.593196.232   298.9 3195.32
  306.253196.232   319.8 3203.47   332.2 3221.69   344.6 3231.85   348.1 3233.24
   381.7 3241.42   398.3 3242.61   406.5 3245.74   431.3 3250.35   480.9 3262.85
   505.7 3270.28   538.7 3271.47   542.9 3272.81   551.1 3278.69   580.2 3288.34
#Mann= 5 ,-1,0
       0      .1       0      50     .12       0     150      .1       0
  288.59    .045       0  306.25      .1       0
Bank Sta=288.59,306.25
XS Rating Curve= 0 ,0
Exp/Cntr(USF)=0,0
Exp/Cntr=0.3,0.1

Type RM Length L Ch R = 1 ,11394   ,264.9,266.4,267.2
XS GIS Cut Line= 2
2217838.98040936579512.2041768262218400.66862647579360.043751602
#Sta/Elev= 30
       0 3220.55    13.7  3217.5    34.4 3215.83   125.6 3212.62   142.1 3213.16
   154.6  3215.9   175.3 3217.28   212.6 3218.83   221.9 3217.37   237.5 3217.17
     254 3219.25   290.4 3203.14   295.5 3200.41   303.8 3193.64  309.87 3190.99
   316.2 3189.79   324.5 3190.99   336.9 3193.05   361.8 3200.15   368.7 3207.09
   378.4 3220.09   388.2 3224.81     398 3227.72   440.4 3236.05   486.1 3252.41
     511 3259.69   521.9  3258.1     535 3259.36   544.7 3267.09   581.9 3282.18
#Mann= 4 ,-1,0
       0     .12       0      30      .1       0  309.87    .045       0
   324.5      .1       0
Bank Sta=309.87,324.5
XS Rating Curve= 0 ,0
Exp/Cntr=0.3,0.1

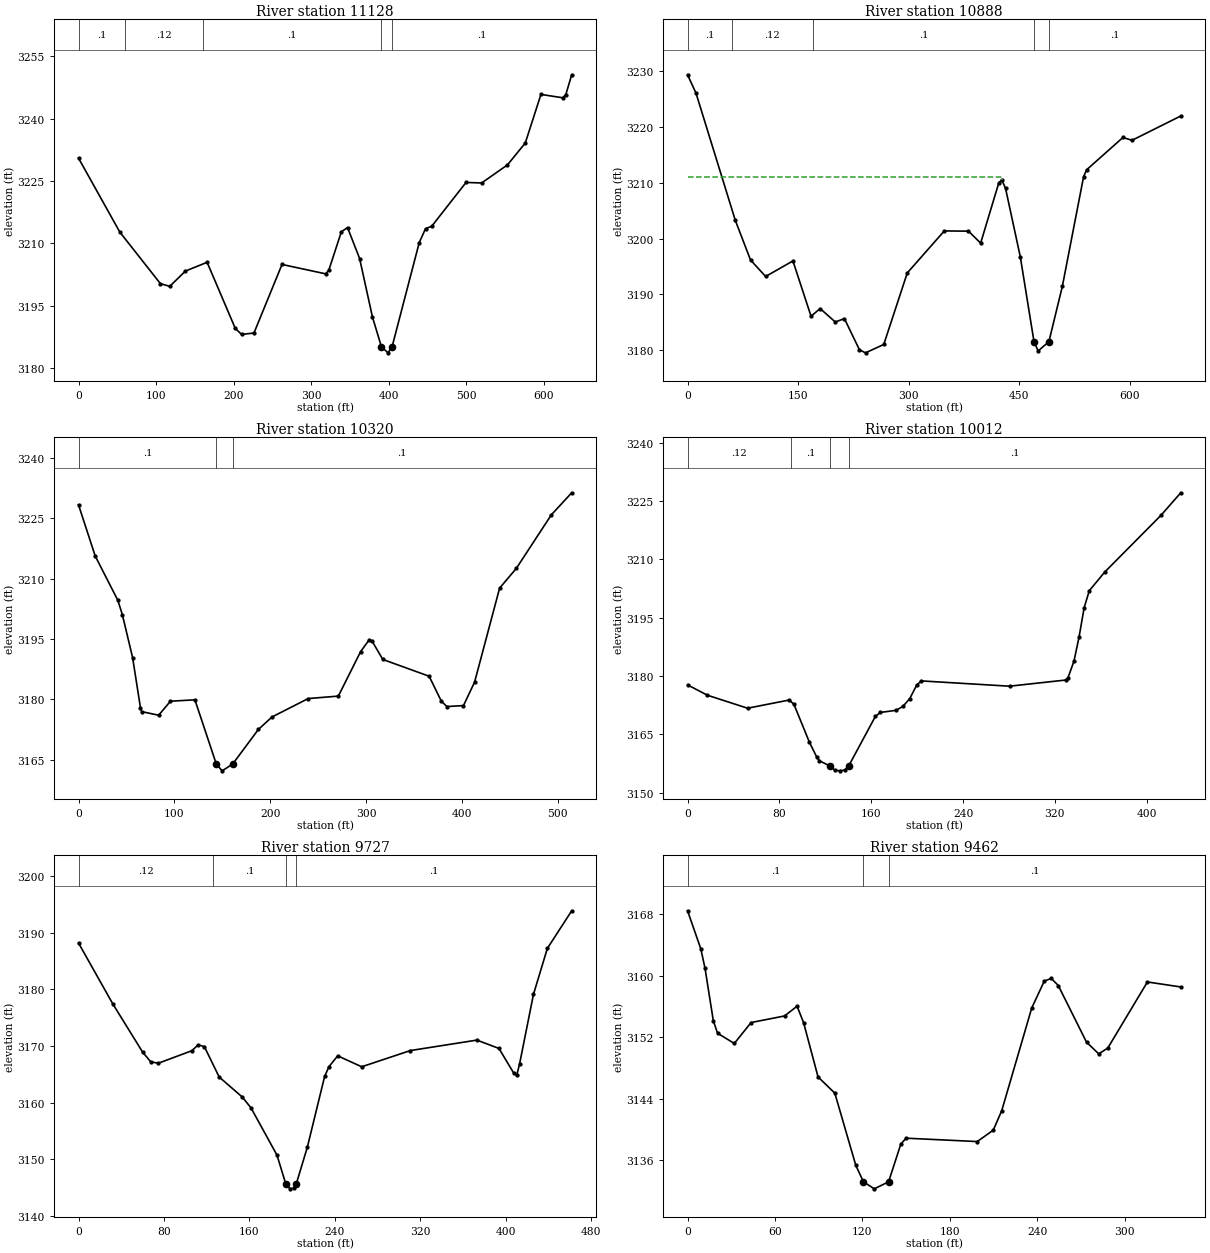
Type RM Length L Ch R = 1 ,11128   ,235.9,240.1,244.2
XS GIS Cut Line= 2
2217811.19853411579727.7656765112218443.71310578579659.111737156
#Sta/Elev= 30
       0  3230.5    53.3 3212.69   105.6 3200.29   117.7 3199.63   137.8  3203.3
   165.9 3205.42   202.2 3189.51   210.3 3188.06   226.3 3188.39   262.5  3204.9
   318.8 3202.64   322.9 3203.54     339 3212.75     347 3213.79   362.6 3206.33
   379.2 3192.22   390.8 3185.04   399.3 3183.62   404.4 3185.02   439.5 3210.16
   447.6 3213.51   455.6  3214.1   499.9 3224.65     520 3224.52   553.3 3228.87
   576.3 3234.14   596.5 3245.84   624.6 3245.03   628.6 3245.82   636.2 3250.57
#Mann= 5 ,-1,0
       0      .1       0      60     .12       0     160      .1       0
   390.8    .045       0   404.4      .1       0
Bank Sta=390.8,404.4
XS Rating Curve= 0 ,0
Exp/Cntr(USF)=0,0
Exp/Cntr=0.3,0.1

Type RM Length L Ch R = 1 ,10888   ,563.2,568.2,572.2
XS GIS Cut Line= 2
2217805.00967768579794.7172086692218456.55467768579945.996208669
#Sta/Elev= 30
       0 3229.39    11.5 3226.08    64.8 3203.27    85.4 3196.18   105.9 3193.22
   142.9 3196.01   167.5 3186.09   179.8 3187.47   200.4 3185.06   212.7 3185.67
   233.2 3180.06   241.4 3179.53   266.1 3181.03     298 3193.86   348.2 3201.39
     381 3201.35   397.5  3199.2   422.1    3210   426.2 3210.55   431.3 3209.01
   451.3 3196.74  469.863181.537   475.5 3179.87  490.053181.531   508.3 3191.44
   537.1  3211.1   541.2 3212.35   590.5 3218.15   602.8 3217.64   668.9    3222
#Mann= 5 ,-1,0
       0      .1       0      60     .12       0     170      .1       0
  469.86    .045       0  490.05      .1       0
#XS Ineff= 2 , 0
           426.2    3211
Permanent Ineff=
       F       F
Bank Sta=469.86,490.05
XS Rating Curve= 0 ,0
Exp/Cntr=0.3,0.1

Type RM Length L Ch R = 1 ,10320   ,307.1,308,305.1
XS GIS Cut Line= 2
2217681.50038389580022.0194253362218116.56748015580296.509094937
#Sta/Elev= 30
       0 3228.34    17.4 3215.62      41  3204.6    45.7 3201.05    56.4 3190.36
    64.6 3177.89    65.9  3176.9    83.6 3176.02    95.9  3179.5   121.4 3179.84
  143.693163.876   149.8 3162.18   160.8 3163.87   187.6 3172.48   201.8 3175.58
   239.6 3180.16     271 3180.77   294.2 3191.82   302.9 3194.68   305.9 3194.55
   317.4 3189.88   365.7 3185.71   378.3 3179.56   384.1 3178.17   401.5 3178.41
   413.1 3184.25   439.2 3207.63   456.6 3212.53   493.2 3225.87   514.4 3231.34
#Mann= 3 ,-1,0
       0      .1       0  143.69    .045       0   160.8      .1       0
Bank Sta=143.69,160.8
XS Rating Curve= 0 ,0
Exp/Cntr=0.3,0.1

Type RM Length L Ch R = 1 ,10012   ,280.7,284.8,290.5
XS GIS Cut Line= 2
2217592.56564373580314.578345499 2217980.0312429580500.275076906
#Sta/Elev= 30
       0 3177.74    17.3 3175.08    52.3 3171.74    88.6 3173.85    92.7 3172.74
     106 3163.12   112.6 3159.15   114.9 3158.22  124.263156.879   128.2 3155.83
   132.6 3155.65   137.1 3155.85  140.393156.904   163.7 3169.67   168.1 3170.66
   181.6  3171.2   187.6 3172.19   193.6 3174.22   199.6 3177.65   203.6 3178.76
   280.5  3177.4     330    3179   331.5 3179.59   336.7 3183.88   341.1 3190.04
   345.5 3197.53     350 3201.93   363.3 3206.68   412.5 3221.32   429.7  3227.1
#Mann= 4 ,-1,0
       0     .12       0      90      .1       0  124.26    .045       0
  140.39      .1       0
Bank Sta=124.26,140.39
XS Rating Curve= 0 ,0
Exp/Cntr=0.3,0.1

Type RM Length L Ch R = 1 ,9727    ,266.3,264.9,261.9
XS GIS Cut Line= 4
 2217477.0395852 580430.951221662217551.05323757580520.274525476
2217571.58947217580646.4010900722217781.96978631580703.354992728
#Sta/Elev= 30
       0 3188.15    32.2 3177.38      60 3168.92    67.6  3167.2    74.8 3166.96
   106.1 3169.16     112  3170.2   117.8 3169.88   131.7 3164.52   153.4 3160.98
   161.5 3159.07   185.8 3150.75   193.9 3145.75     198 3144.81     202 3144.95
  203.93 3145.74   214.2 3152.14   230.4 3164.63   234.4 3166.33   242.6 3168.26
   265.1 3166.33   310.7 3169.19   372.9 3171.03   393.6 3169.56   407.5 3165.18
   410.2  3164.8   412.9 3166.84   425.9 3179.11   438.9  3187.2   461.7 3193.83
#Mann= 4 ,-1,0
       0     .12       0     126      .1       0   193.9    .045       0
  203.93      .1       0
Bank Sta=193.9,203.93
XS Rating Curve= 0 ,0
Exp/Cntr=0.3,0.1

Type RM Length L Ch R = 1 ,9462    ,294.3,293.9,292.9
XS GIS Cut Line= 2
2217273.15776395 580631.546251452217465.15303825580910.434800954
#Sta/Elev= 30
       0 3168.44     9.1 3163.49      12 3160.95    17.7 3154.13    20.6 3152.51
    32.1 3151.18    43.6  3153.9    66.6 3154.76    75.2 3156.03    79.7 3153.86
    89.6 3146.82   101.1 3144.72   115.5 3135.33  120.71 3133.19   128.2 3132.27
     138 3133.18   146.4 3138.08     150 3138.86   198.9 3138.42   209.9 3139.91
   215.7 3142.44   236.3  3155.8   244.9 3159.29   249.7 3159.64   254.5 3158.72
   273.9 3151.35   282.3 3149.83   288.5 3150.58   315.7 3159.18   338.6 3158.53
#Mann= 3 ,-1,0
       0      .1       0  120.71    .045       0     138      .1       0
Bank Sta=120.71,138
XS Rating Curve= 0 ,0
Exp/Cntr(USF)=0,0
Exp/Cntr=0.3,0.1

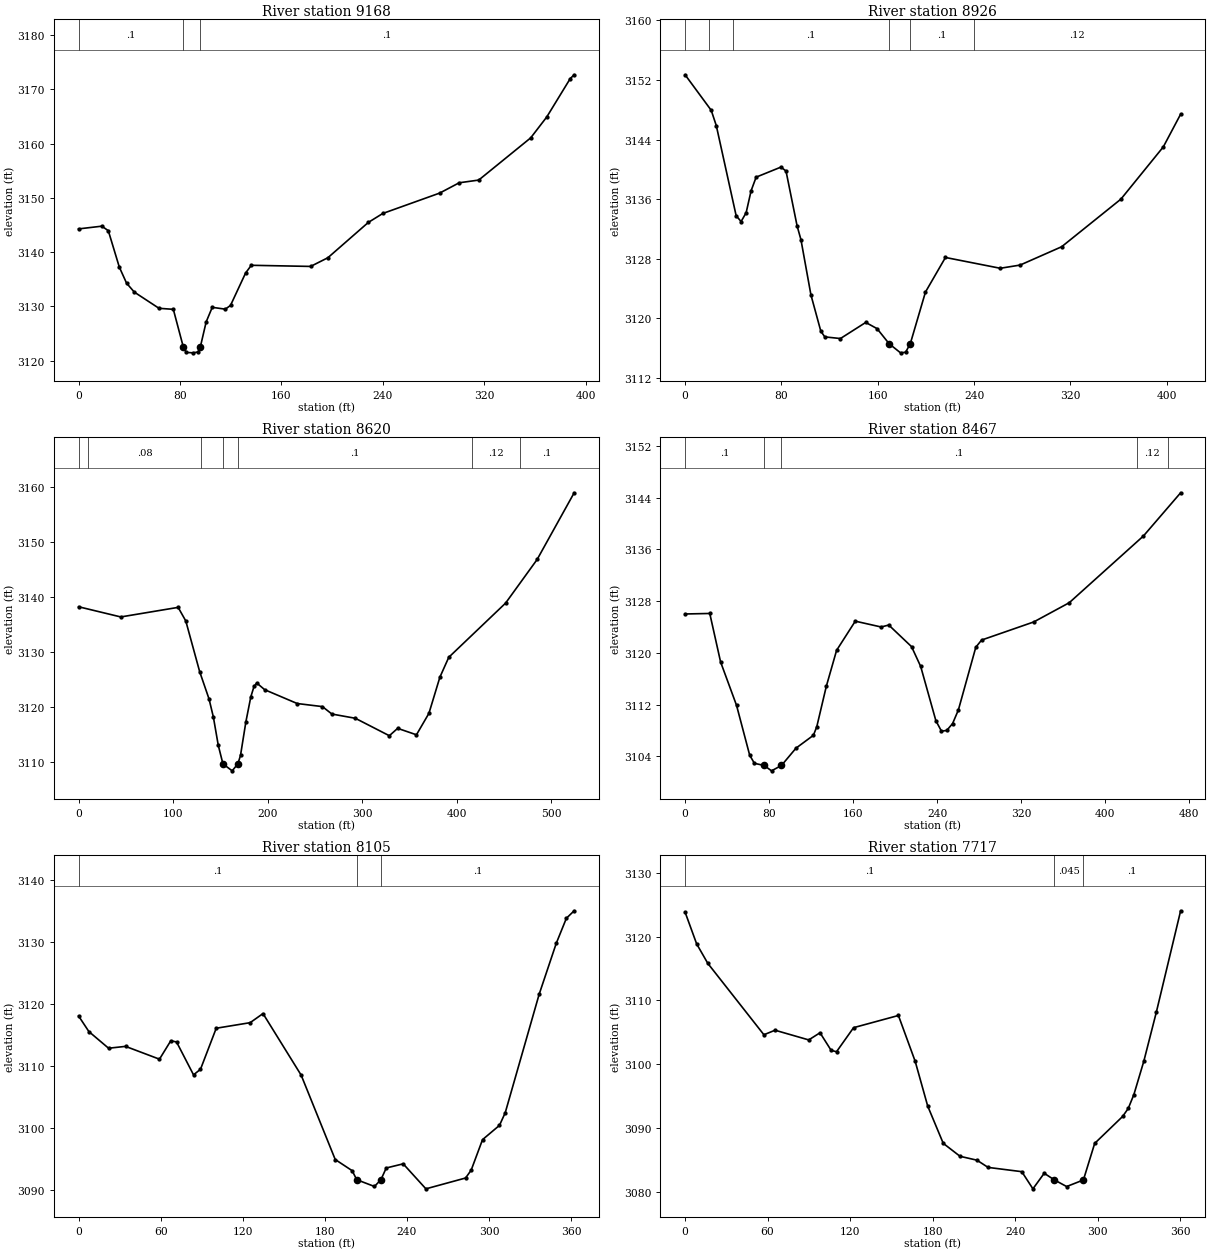
Type RM Length L Ch R = 1 ,9168    ,239,242.4,245.8
XS GIS Cut Line= 2
2217069.28132127580858.901053038 2217313.6651694581163.934907275
#Sta/Elev= 30
       0 3144.29    18.3 3144.79    23.4 3143.96    32.1 3137.24    37.8 3134.29
    43.9 3132.64    63.4 3129.65    74.7 3129.46    82.63122.498    84.9 3121.52
    90.1 3121.44    94.2 3121.59   95.96 3122.48   100.6 3127.14   105.4 3129.83
   115.7 3129.49   119.8 3130.18   131.7 3136.15   136.2 3137.58     183 3137.37
   196.6 3138.97   228.5 3145.48   239.9 3147.13   284.8 3150.89   300.2 3152.79
   315.6 3153.29   356.6 3161.07   369.3 3164.93   387.8    3172   390.9  3172.7
#Mann= 3 ,-1,0
       0      .1       0    82.6    .045       0   95.96      .1       0
Bank Sta=82.6,95.96
XS Rating Curve= 0 ,0
Exp/Cntr(USF)=0,0
Exp/Cntr=0.3,0.1

Type RM Length L Ch R = 1 ,8926    ,307,305.2,301
XS GIS Cut Line= 3
2216875.43827192580884.178187643 2216952.3244188581175.015407367
2217010.06892951581269.483900256
#Sta/Elev= 30
       0 3152.71    21.7 3147.94    25.9 3145.89    42.4 3133.79    46.5 3133.01
    50.7  3134.2    54.8 3137.14      59 3138.97    79.6 3140.32    83.8 3139.79
      93 3132.43    96.2 3130.58   104.5 3123.16   112.7  3118.3     116 3117.53
     129 3117.31     150 3119.47   159.4 3118.64  169.463116.609   178.9 3115.39
   183.1 3115.47     187 3116.61   199.6 3123.55   216.2 3128.19   261.7 3126.74
   278.2 3127.17   312.7 3129.63   361.9 3136.02   397.1 3143.03   411.5 3147.42
#Mann= 6 ,-1,0
       0      .1       0      20     .12       0      40      .1       0
  169.46    .045       0     187      .1       0     240     .12       0
Bank Sta=169.46,187
XS Rating Curve= 0 ,0
Exp/Cntr=0.3,0.1

Type RM Length L Ch R = 1 ,8620    ,151.4,153.5,147.9
XS GIS Cut Line= 3
2216557.52757223581016.8889039042216695.04694502581209.580335982
2216926.43710618581380.478078977
#Sta/Elev= 30
       0 3138.18    44.6 3136.33   105.3 3138.07   113.4  3135.6   128.1 3126.38
     138 3121.43   142.6 3118.13   147.8 3112.98   152.7 3109.64   162.5 3108.37
  168.53 3109.65   171.3 3111.17     177 3117.28   182.2 3121.81   185.6  3123.7
   188.5 3124.33   196.9 3123.11   231.3  3120.6     258 3120.04     268 3118.69
   292.8 3117.92   328.8 3114.75   337.6 3116.09   357.5 3114.92   370.7 3118.82
   382.3 3125.39   391.7    3129   451.8 3138.84   485.2 3146.77   524.4 3158.89
#Mann= 7 ,-1,0
       0      .1       0      10     .08       0     130      .1       0
   152.7    .045       0  168.53      .1       0  416.73     .12       0
  466.73      .1       0
Bank Sta=152.7,168.53
XS Rating Curve= 0 ,0
Exp/Cntr=0.3,0.1

Type RM Length L Ch R = 1 ,8467    ,355.9,362.3,364.2
XS GIS Cut Line= 2
2216447.65889037581120.4533963792216789.50114556581445.893763661
#Sta/Elev= 30
       0    3126    23.5 3126.08    33.8 3118.59      49 3111.88    61.5 3104.19
      66 3102.92   75.33 3102.59    82.3 3101.76    91.83102.591   105.6 3105.26
   122.2 3107.25   125.4 3108.56   134.5 3114.82   144.3 3120.38   162.1 3124.89
   186.7 3123.99     194 3124.29   215.7 3120.95   224.4 3117.89   238.9 3109.49
   244.2 3107.89   249.2    3108   254.8 3109.07   260.3 3111.17   276.9 3120.86
   282.4 3121.97   332.1 3124.77   365.9 3127.74   436.6 3138.06     472 3144.73
#Mann= 5 ,-1,0
       0      .1       0   75.33    .045       0    91.8      .1       0
     430     .12       0     460      .1       0
Bank Sta=75.33,91.8
XS Rating Curve= 0 ,0
Exp/Cntr(USF)=0,0
Exp/Cntr=0.3,0.1

Type RM Length L Ch R = 1 ,8105    ,385.7,387.1,387.9
XS GIS Cut Line= 2
2216240.07022537581164.0779169872216334.45482322581513.913290321
#Sta/Elev= 30
       0 3118.09     7.5 3115.58    21.9 3112.89    34.3 3113.19    59.1 3111.12
    67.4  3114.1    71.6  3113.9      84 3108.59    89.1 3109.49   100.6 3116.12
   125.4 3117.02   134.8 3118.49   162.7 3108.54   187.6 3094.91     200  3093.1
   203.3 3091.65   216.3 3090.55  221.073091.676   224.9 3093.54   237.3 3094.21
   253.9 3090.17   282.9 3091.92     287 3093.19   295.3 3098.12   307.7 3100.43
   311.9 3102.47   336.7 3121.61   349.2 3129.84   356.6 3133.89   362.3  3135.1
#Mann= 3 ,-1,0
       0      .1       0   203.3    .045       0  221.07      .1       0
Bank Sta=203.3,221.07
XS Rating Curve= 0 ,0
Exp/Cntr=0.3,0.1

Type RM Length L Ch R = 1 ,7717    ,333.2,334.1,332.4
XS GIS Cut Line= 2
2215899.28156323581252.9464936012215968.35025878581606.527625572
#Sta/Elev= 30
       0 3123.82     8.4 3118.85    16.5  3115.8    57.3 3104.61    65.4 3105.32
    89.9  3103.8    98.1 3104.92   106.2 3102.16   110.1 3101.95   122.5 3105.72
   155.1 3107.63   167.3 3100.44   176.4 3093.43   187.7 3087.59   199.9 3085.56
   212.2 3084.95   220.3 3083.82   244.8 3083.15   252.9 3080.46   261.1  3082.9
   268.53081.861   277.4 3080.82   289.6 3081.85   297.8 3087.58   318.1  3091.8
   322.2 3093.06   326.3 3095.23   333.5 3100.44   342.6 3108.12   360.3 3124.04
#Mann= 3 ,-1,0
       0      .1       0   268.5    .045       0   289.6      .1       0
Bank Sta=268.5,289.6
XS Rating Curve= 0 ,0
Exp/Cntr=0.3,0.1

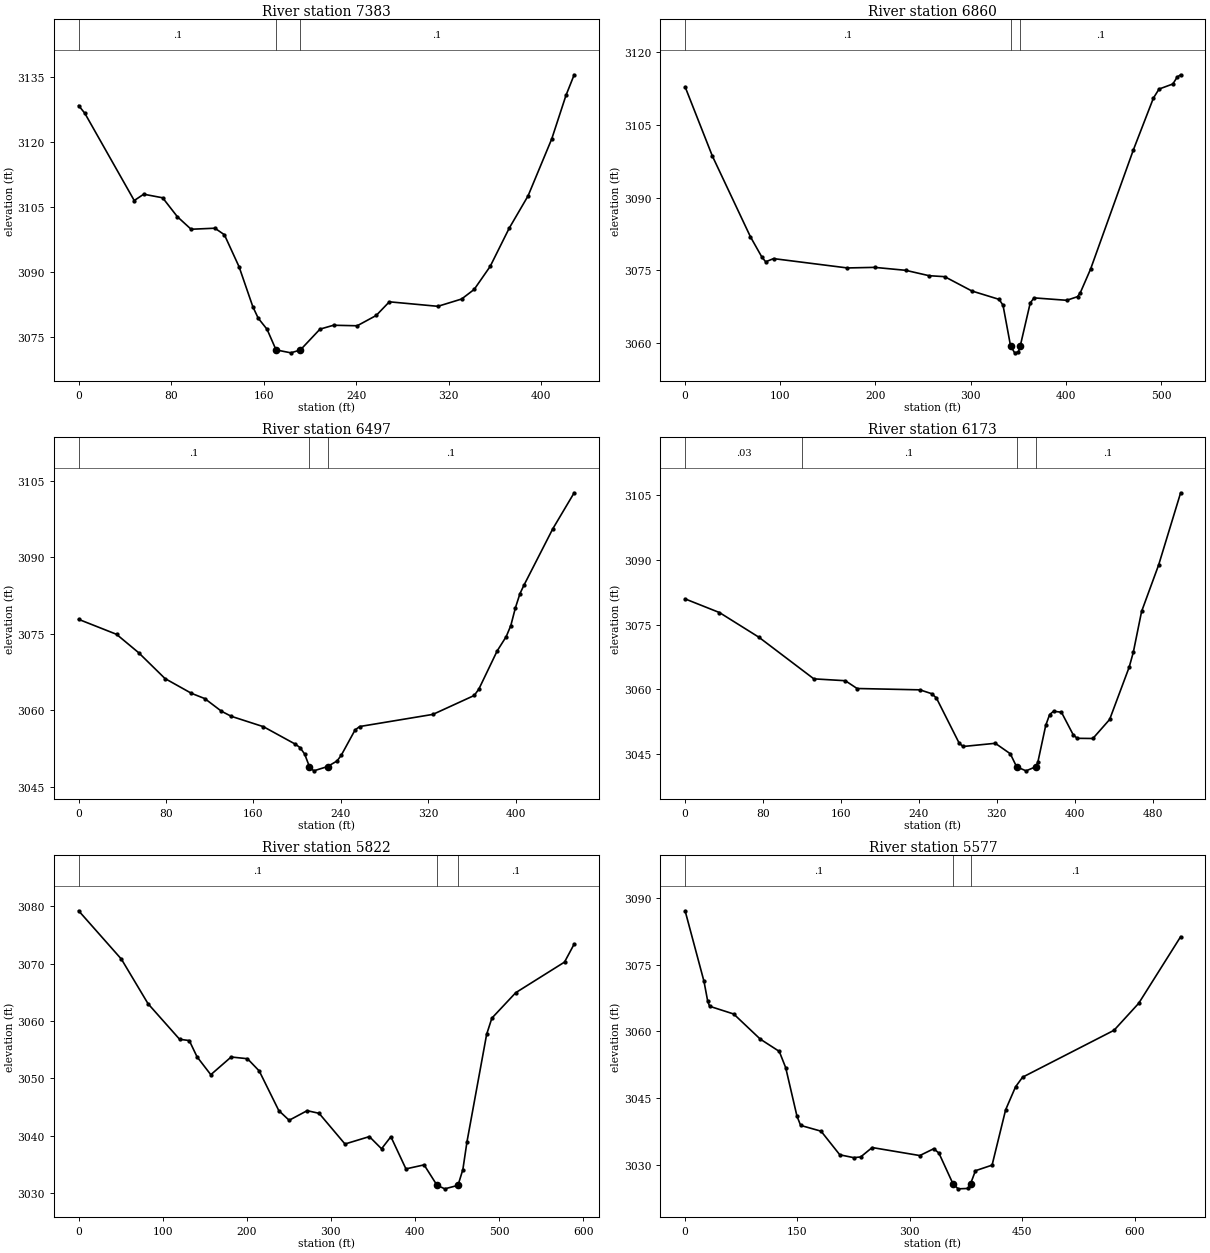
Type RM Length L Ch R = 1 ,7383    ,520,522.9,521
XS GIS Cut Line= 2
2215600.63477011 581262.32224727  2215696.986091581680.044403193
#Sta/Elev= 30
       0 3128.35     5.3  3126.6    48.1 3106.43    56.3 3107.89    72.7 3107.06
    85.4  3102.7    97.3  3099.8   117.9 3100.04   126.1 3098.53   138.8 3091.14
   150.7 3081.92   155.4 3079.25     163 3076.71   170.8 3071.95   183.6 3071.27
   191.8 3071.93   208.8 3076.74   220.5 3077.64     241 3077.52   257.4 3079.89
   268.8 3083.05   310.8 3082.01   331.3 3083.69   342.2 3085.91     356 3091.21
   372.4    3100   388.8  3107.5   409.3 3120.66   421.6  3130.7   428.7 3135.46
#Mann= 3 ,-1,0
       0      .1       0   170.8    .045       0   191.8      .1       0
Bank Sta=170.8,191.8
XS Rating Curve= 0 ,0
Exp/Cntr(USF)=0,0
Exp/Cntr=0.3,0.1

Type RM Length L Ch R = 1 ,6860    ,366.7,363.4,360.5
XS GIS Cut Line= 4
2215259.67704025581312.5808609852215259.48046278581390.414406518
2215192.81950093581711.0276042832215247.81467971581812.341751473
#Sta/Elev= 30
       0  3112.9    28.6 3098.62    68.6 3081.94    80.7 3077.72    84.7 3076.76
    92.9 3077.42   170.5 3075.49   199.1 3075.61   231.8    3075   256.3 3073.89
   272.7 3073.69   301.3 3070.73   329.9    3069     334 3067.79   341.93059.411
   346.2 3057.96   350.2 3058.13  352.13  3059.4   362.6 3068.27   366.6 3069.31
   400.9 3068.81   412.3 3069.56   415.3 3070.42     426 3075.26     471  3099.9
     492 3110.57   497.9 3112.43   512.4 3113.48     517 3114.91   520.6 3115.38
#Mann= 3 ,-1,0
       0      .1       0   341.9    .045       0  352.13      .1       0
Bank Sta=341.9,352.13
XS Rating Curve= 0 ,0
Exp/Cntr=0.3,0.1

Type RM Length L Ch R = 1 ,6497    ,318.8,324.2,323.4
XS GIS Cut Line= 3
2214815.67593201581458.7400141172214833.73139434581594.091621827
2214929.43454146581896.436000587
#Sta/Elev= 30
       0 3077.84    34.7 3074.91    54.9 3071.32    79.1 3066.25   103.3 3063.36
   115.5 3062.33   130.8 3059.85   139.8 3058.86   169.2 3056.83   198.5  3053.4
   202.7 3052.74   206.9 3051.49   211.33049.019   215.3 3048.19   227.9 3049.03
   236.6 3050.12   240.5 3051.26   253.1 3056.19   257.3 3056.86   324.4 3059.24
   362.2 3062.94   366.4 3064.18   383.2 3071.66   391.5 3074.47   395.7 3076.63
   399.9  3080.1   404.1 3082.89   407.6 3084.47   434.1 3095.55   453.7 3102.61
#Mann= 3 ,-1,0
       0      .1       0   211.3    .045       0   227.9      .1       0
Bank Sta=211.3,227.9
XS Rating Curve= 0 ,0
Exp/Cntr=0.3,0.1

Type RM Length L Ch R = 1 ,6173    ,336.2,350.9,355
XS GIS Cut Line= 3
2214557.27265507581494.1801940612214615.06854324581926.043914007
2214639.15016331581995.077891544
#Sta/Elev= 30
       0 3080.92    35.3 3077.76    75.7 3072.07   132.2 3062.43   164.5    3062
   176.6  3060.2   241.1 3059.89   253.2    3059     258 3058.02   281.5 3047.52
   285.5 3046.79   318.5 3047.53   333.9 3045.11  340.413042.085   350.1 3041.16
  359.843042.084   362.2 3043.17   370.3 3051.69   374.3 3054.18   378.3 3054.93
   386.4 3054.72   398.5  3049.5   402.6 3048.68   418.7 3048.64   435.9 3053.04
     456 3065.16   460.2 3068.58   468.7 3078.01   486.2 3088.76   508.8 3105.46
#Mann= 4 ,-1,0
       0     .03       0     120      .1       0  340.41    .045       0
  359.84      .1       0
Bank Sta=340.41,359.84
XS Rating Curve= 0 ,0
Exp/Cntr(USF)=0,0
Exp/Cntr=0.3,0.1

Type RM Length L Ch R = 1 ,5822    ,236.3,245.1,247.5
XS GIS Cut Line= 2
2214512.87850521581515.1059690682214181.70737426582002.658670194
#Sta/Elev= 30
       0 3079.18    50.9 3070.76    82.6    3063   120.1 3056.82   131.6  3056.6
   140.8 3053.78   157.2 3050.66   181.4 3053.74   200.8 3053.44   214.8 3051.31
   238.1 3044.41   250.4 3042.73   271.8  3044.4     286 3043.94   316.8  3038.6
   345.8 3039.89   360.3 3037.77   371.4 3039.87   389.3 3034.27   410.9 3034.97
  426.24 3031.43   435.5  3030.8   451.2 3031.41     457 3034.15   461.9 3038.98
   485.3 3057.69   491.5  3060.5   519.9 3064.93   577.9 3070.25   589.4 3073.39
#Mann= 3 ,-1,0
       0      .1       0  426.24    .045       0   451.2      .1       0
Bank Sta=426.24,451.2
XS Rating Curve= 0 ,0
Exp/Cntr=0.3,0.1

Type RM Length L Ch R = 1 ,5577    ,354.9,348.8,343.1
XS GIS Cut Line= 4
2214399.52804431581428.8240761192214279.97232245581591.758422718
2214084.23950349581707.0820836222213962.56775116581904.930933063
#Sta/Elev= 30
       0 3087.07    25.2 3071.24    30.2 3066.76    32.7 3065.64    64.9  3063.9
   100.3 3058.27   125.7 3055.51   134.3 3051.85   149.3    3041   154.2  3038.9
   181.5  3037.6   206.5  3032.3   225.1 3031.66   234.4 3031.82   249.7 3033.93
   313.3 3032.13   331.9 3033.66   338.8 3032.69  357.463025.839   364.4 3024.66
   378.3 3024.75   381.2 3025.85   387.6 3028.73   409.8 3029.98   427.9 3042.41
   441.1 3047.55   450.5 3049.72   572.6 3060.25   605.5  3066.3   661.5 3081.25
#Mann= 3 ,-1,0
       0      .1       0  357.46    .045       0   381.2      .1       0
Bank Sta=357.46,381.2
XS Rating Curve= 0 ,0
Exp/Cntr(USF)=0,0
Exp/Cntr=0.3,0.1