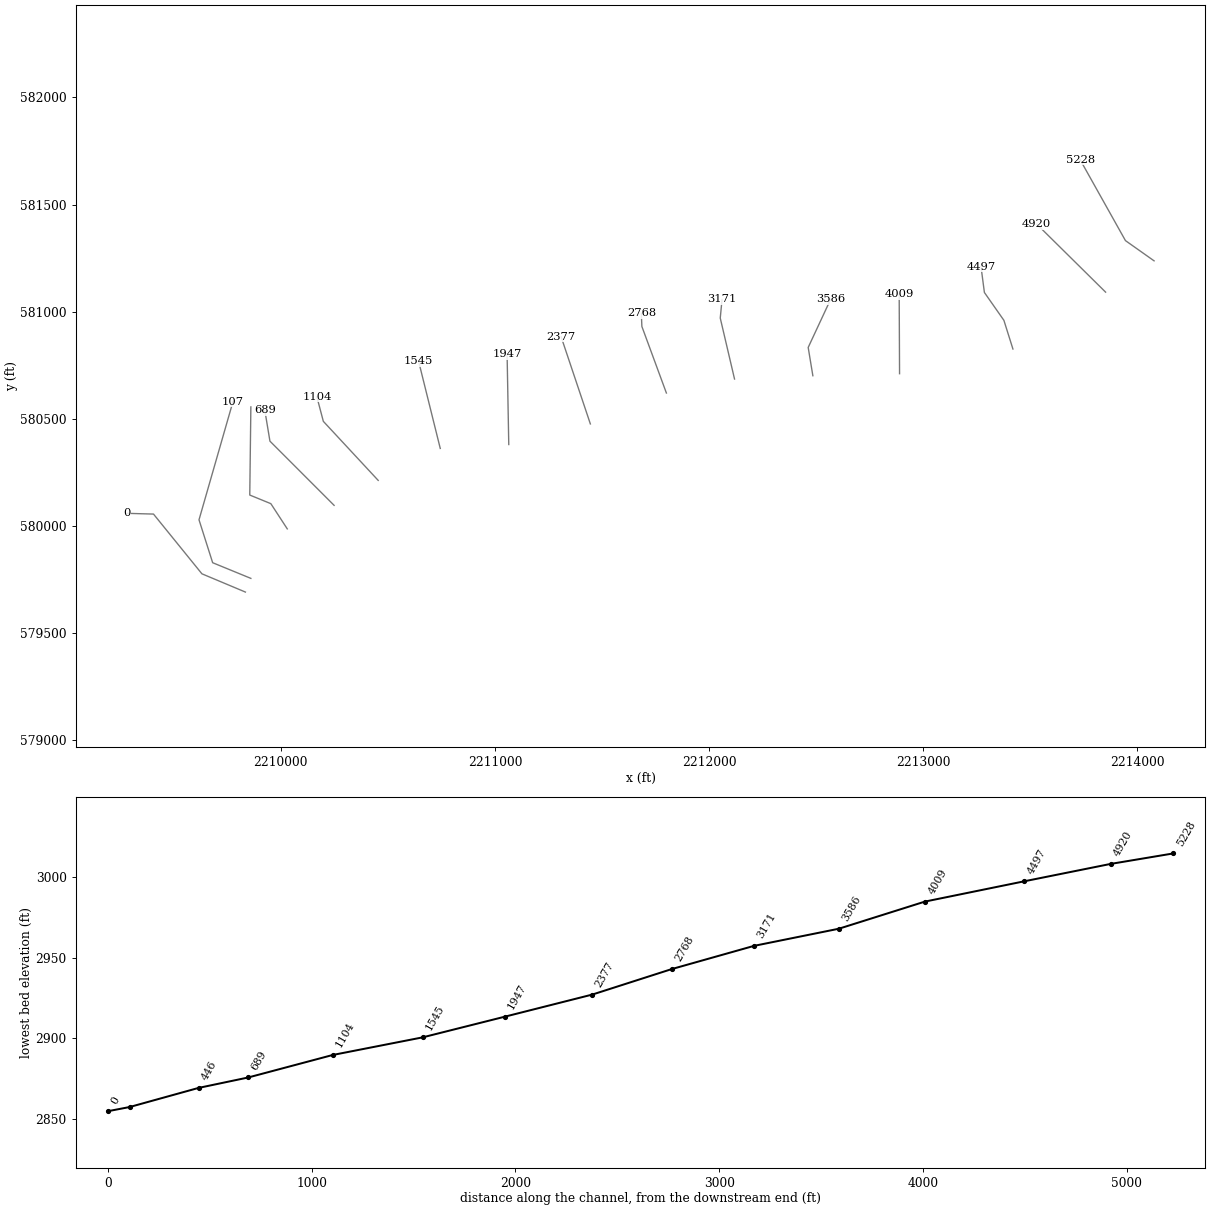
HEC-RAS study COALBNKFK.prj: COALBNKFK

--- COALBNKFK.g01 (geometry) --- (continued)

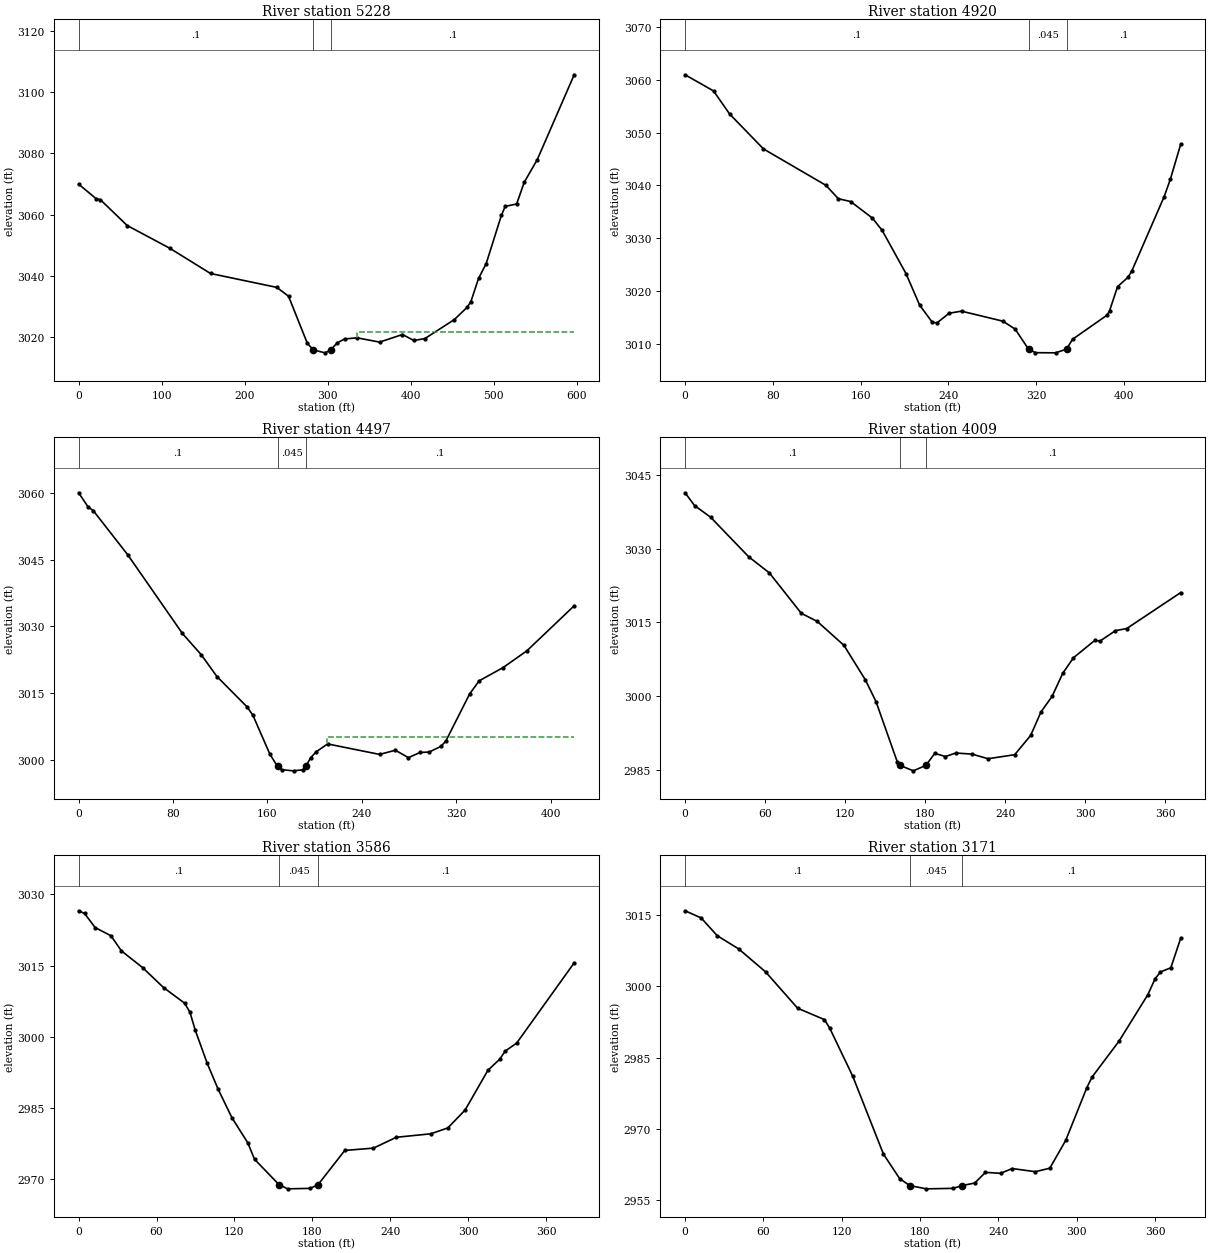
Type RM Length L Ch R = 1 ,5228    ,301.1,308,313.3
XS GIS Cut Line= 3
2214077.67853982581237.1466236822213944.05995014581331.583076306
 2213732.2266884581709.691449793
#Sta/Elev= 30
       0 3069.93    21.2 3065.16    26.3 3064.83    58.5 3056.41   109.6 3049.01
   158.9 3040.72   238.8 3036.17   252.9 3033.27   275.5  3017.9  282.77 3015.71
   296.9 3014.77   303.6 3015.71   311.6 3018.04   320.5  3019.3   335.2 3019.69
   362.6 3018.28   390.1 3020.76   403.9 3018.81   417.1 3019.43   452.7 3025.66
   468.1 3029.69   472.6 3031.56   481.8  3039.1     491 3043.96   509.3 3059.72
   513.9 3062.67   527.7 3063.45   536.8 3070.54   552.6    3078     597 3105.71
#Mann= 3 ,-1,0
       0      .1       0  282.77    .045       0   303.6      .1       0
#XS Ineff= 2 , 0
                          335.03         3021.67
Permanent Ineff=
       F       F
Bank Sta=282.77,303.6
XS Rating Curve= 0 ,0
Exp/Cntr=0.3,0.1

Type RM Length L Ch R = 1 ,4920    ,425.5,423,422.5
XS GIS Cut Line= 2
2213851.34149264581090.9797236172213530.09153006581408.356983488
#Sta/Elev= 30
       0 3060.96    25.9  3057.9    40.6 3053.52    71.4 3046.91   128.3 3040.01
   139.7 3037.46   150.9 3036.93   170.7 3033.79   179.6 3031.46   201.3 3023.28
   213.7 3017.31   225.1 3014.09   229.4  3013.9   240.6 3015.76   251.9 3016.15
   289.5 3014.26   300.8 3012.75  312.963008.943   319.3 3008.28   337.6 3008.25
  347.593008.943   353.1 3010.82   384.5 3015.39   386.8  3016.2   394.1 3020.79
   403.7 3022.58   407.2 3023.81   436.6 3037.87   442.2 3041.14   451.6 3047.75
#Mann= 3 ,-1,0
       0      .1       0  312.96    .045       0  347.59      .1       0
Bank Sta=312.96,347.59
XS Rating Curve= 0 ,0
Exp/Cntr=0.3,0.1

Type RM Length L Ch R = 1 ,4497    ,495.7,488.4,482.2
XS GIS Cut Line= 4
2213418.58613523580825.3696402562213376.40258718580959.331201457
2213285.37406331581089.3719498422213269.66830761581208.940879486
#Sta/Elev= 30
       0  3060.1     8.2 3056.85    12.4 3056.08    41.7  3046.1    87.9 3028.42
   103.8 3023.65   117.2 3018.71   142.7 3011.88   147.6 3010.02     162 3001.24
  168.522998.474     172 2997.73   182.1 2997.48   189.7 2997.71  192.442998.475
   196.6 3000.45   201.3 3001.77   210.9 3003.54     255 3001.18   268.3 3002.12
   279.4 3000.45   289.2 3001.62     297 3001.71   307.1 3003.02   311.1 3004.21
   331.3 3014.82   339.3 3017.75   359.5 3020.72   379.7  3024.5   419.8 3034.65
#Mann= 3 ,-1,0
       0      .1       0  168.52    .045       0  192.44      .1       0
#XS Ineff= 2 , 0
                           210.6            3005
Permanent Ineff=
       F       F
Bank Sta=168.52,192.44
XS Rating Curve= 0 ,0
Exp/Cntr=0.3,0.1

Type RM Length L Ch R = 1 ,4009    ,428.4,422.1,414.4
XS GIS Cut Line= 2
2212889.16496052580710.1122763832212887.44937325581081.569504939
#Sta/Elev= 30
       0 3041.36     7.1 3038.76    19.1  3036.4    47.8 3028.32    63.1  3025.1
    87.1 3016.87    99.1 3015.21   119.1 3010.35   135.1 3003.36   143.1 2998.94
   159.1 2986.65  161.062985.967   171.1 2984.85  180.542985.967   187.2 2988.41
   195.1 2987.76     203 2988.47   215.1 2988.25   227.1 2987.31   247.1 2988.13
   259.1 2992.06   266.8 2996.82   275.1 2999.97   283.1 3004.66   291.1 3007.82
   307.1 3011.35   311.1 3011.23   322.6 3013.33   331.1 3013.77   371.5 3021.07
#Mann= 3 ,-1,0
       0      .1       0  161.06    .045       0  180.54      .1       0
Bank Sta=161.06,180.54
XS Rating Curve= 0 ,0
Exp/Cntr=0.3,0.1

Type RM Length L Ch R = 1 ,3586    ,404.9,415.8,427.2
XS GIS Cut Line= 3
2212484.29623277580700.618496771 2212462.5158191580832.659848259
2212567.22796464581057.290873294
#Sta/Elev= 30
       0 3026.53     4.6 3025.96    12.7    3023    24.9 3021.27      33 3018.08
    49.2 3014.59    65.4 3010.37    81.6 3007.09    85.7 3005.21    89.8 3001.41
    99.1 2994.39   107.3 2989.07   118.1 2982.96   130.3  2977.7   135.5 2974.23
  154.272968.917   160.9 2968.01   178.5 2968.11  184.492968.915     205 2976.09
   227.1 2976.58   244.7 2978.86   271.2 2979.59   284.4 2980.83   297.7  2984.6
   315.3 2992.98   324.2 2995.24   328.6 2997.01   337.4 2998.68   381.7 3015.57
#Mann= 3 ,-1,0
       0      .1       0  154.27    .045       0  184.49      .1       0
Bank Sta=154.27,184.49
XS Rating Curve= 0 ,0
Exp/Cntr=0.3,0.1

Type RM Length L Ch R = 1 ,3171    ,400.1,403.2,399.3
XS GIS Cut Line= 3
2212118.54472129580685.2510518672212051.87045316 580969.88848645
2212060.26285445581056.623538585
#Sta/Elev= 30
       0  3015.9    12.3 3014.39    24.6 3010.66      41 3007.88    61.6 3003.05
    86.2 2995.39   106.7    2993   110.8 2991.18   128.4 2981.07   151.9 2964.69
   164.3 2959.54  172.012958.068   184.8 2957.38   205.3 2957.48  212.192958.067
   221.8  2958.6     230 2960.84   241.6 2960.65   250.5 2961.65   268.2 2960.99
   279.3 2961.72   291.5 2967.58   307.7  2978.7   311.7 2980.92   332.3 2988.46
   354.3  2998.2   359.9 3001.57     364 3003.02     372 3003.91   379.5 3010.09
#Mann= 3 ,-1,0
       0      .1       0  172.01    .045       0  212.19      .1       0
Bank Sta=172.01,212.19
XS Rating Curve= 0 ,0
Exp/Cntr=0.3,0.1

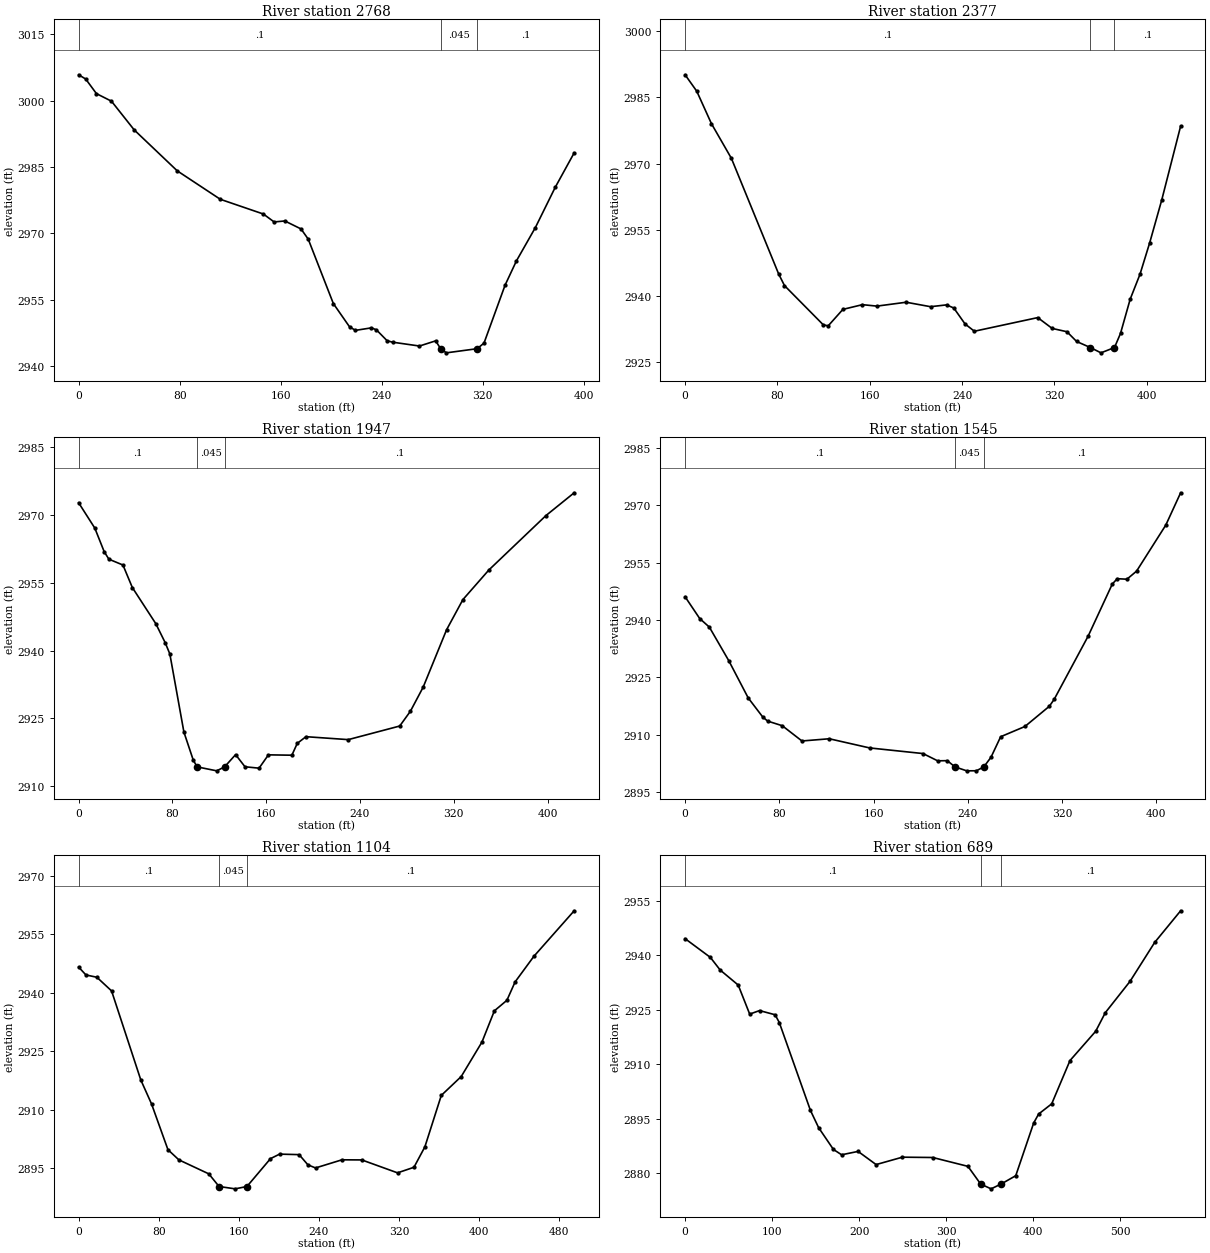
Type RM Length L Ch R = 1 ,2768    ,390.5,390.4,389.6
XS GIS Cut Line= 3
2211800.30871675580619.9248481712211685.87285817580930.722236812
 2211683.2720432580991.841388553
#Sta/Elev= 30
       0 3005.85     5.6 3004.89    14.1 3001.59      26 2999.88      44 2993.39
    78.1 2984.13   112.2  2977.7   146.3 2974.37   154.8 2972.58   163.3  2972.8
   176.1    2971   181.8  2968.7   201.7 2954.13   214.5 2948.88   219.2 2948.07
   231.9 2948.64   235.8 2948.19   244.3 2945.72   248.6  2945.4   269.9 2944.53
   282.7  2945.7  286.682943.926   291.2 2942.99  315.612943.928     321 2945.19
   337.7  2958.3   346.7 2963.79   361.7 2971.32   377.4 2980.41   392.4  2988.2
#Mann= 3 ,-1,0
       0      .1       0  286.68    .045       0  315.61      .1       0
Bank Sta=286.68,315.61
XS Rating Curve= 0 ,0
Exp/Cntr(USF)=0,0
Exp/Cntr=0.3,0.1

Type RM Length L Ch R = 1 ,2377    ,437.9,429.7,429
XS GIS Cut Line= 2
2211445.29747365580475.5796174632211308.75468785580882.607159909
#Sta/Elev= 30
       0 2990.11    10.1 2986.39    22.8 2979.05    40.1 2971.19    81.1 2944.97
    86.1 2942.37   119.8 2933.46     124 2933.26   136.7 2936.98   153.6 2938.05
   166.2 2937.72   191.5  2938.6   212.6 2937.59   226.5    2938   232.8 2937.29
   242.5 2933.69   250.6 2932.03   305.5 2935.12     318 2932.67   330.8 2931.92
   339.2 2929.71  351.042928.345   360.3 2927.14     3722928.344   377.2 2931.53
   385.6  2939.3   394.1 2944.94   402.5 2952.07   412.9 2961.73   429.3 2978.49
#Mann= 3 ,-1,0
       0      .1       0  351.04    .045       0     372      .1       0
Bank Sta=351.04,372
XS Rating Curve= 0 ,0
Exp/Cntr(USF)=0,0
Exp/Cntr=0.3,0.1

Type RM Length L Ch R = 1 ,1947    ,399.2,402.7,405.2
XS GIS Cut Line= 2
2211064.27808089580379.3494636592211056.47563598580801.981895911
#Sta/Elev= 30
       0 2972.73    13.8 2967.12    21.8  2961.9    25.8 2960.24    37.8 2958.95
    45.8 2953.97    65.8 2945.98    73.8 2941.78    77.8 2939.27    89.8 2921.97
    97.8 2915.75  101.092914.267   117.8 2913.39  124.512914.272   133.9 2916.98
   141.9 2914.29   153.9 2913.98   161.9 2916.93   181.9 2916.85   186.5 2919.47
   193.9 2920.95     230  2920.3   273.9 2923.31     283 2926.58   293.9 2931.92
   313.9 2944.64   327.8  2951.3   349.9 2957.84   398.6 2969.89   422.7 2974.94
#Mann= 3 ,-1,0
       0      .1       0  101.09    .045       0  124.51      .1       0
Bank Sta=101.09,124.51
XS Rating Curve= 0 ,0
Exp/Cntr(USF)=0,0
Exp/Cntr=0.3,0.1

Type RM Length L Ch R = 1 ,1545    ,433,441.1,445.4
XS GIS Cut Line= 2
2210744.37783986580361.1437588852210642.94605612580769.471708814
#Sta/Elev= 30
       0  2946.1    12.4 2940.41    20.6 2938.16    37.1 2929.37    53.6 2919.63
      66 2914.62    70.1 2913.58    82.5 2912.37    99.2 2908.38   122.4 2908.96
   156.7 2906.56     202 2905.09   214.4 2903.19   222.6 2903.23   229.12901.603
   239.1 2900.57   247.3 2900.59   253.62901.603   259.7 2904.12   267.9 2909.49
   288.5 2912.17   309.2 2917.45   313.3 2919.25   342.1 2935.76   362.7 2949.44
   366.9 2950.83   375.1 2950.69   383.3 2952.81   408.1 2964.85   420.7  2973.3
#Mann= 3 ,-1,0
       0      .1       0   229.1    .045       0   253.6      .1       0
Bank Sta=229.1,253.6
XS Rating Curve= 0 ,0
Exp/Cntr(USF)=0,0
Exp/Cntr=0.3,0.1

Type RM Length L Ch R = 1 ,1104    ,410.9,414.7,408.4
XS GIS Cut Line= 3
2210454.55817067580211.8639570872210198.38288017 580487.59578132
2210168.11557389580602.233325807
#Sta/Elev= 30
       0 2946.61     7.3 2944.59    18.2    2944    32.9 2940.49    62.1  2917.6
    72.8 2911.46    89.2 2899.69   100.1 2897.08     130 2893.48  140.26 2890.23
   156.3 2889.63   168.1 2890.23   191.6 2897.39   200.7 2898.55   220.2 2898.42
     229 2895.79   236.6    2895     263 2897.09   282.8 2897.06   318.5 2893.74
   334.9 2895.17   345.8 2900.42   362.2 2913.64   382.1 2918.49   402.8 2927.34
   415.2 2935.37   427.7 2938.07   435.9  2942.8   454.7 2949.39   494.9 2961.08
#Mann= 3 ,-1,0
       0      .1       0  140.26    .045       0   168.1      .1       0
Bank Sta=140.26,168.1
XS Rating Curve= 0 ,0
Exp/Cntr(USF)=0,0
Exp/Cntr=0.3,0.1

Type RM Length L Ch R = 1 ,689     ,238.2,243.3,247.9
XS GIS Cut Line= 3
2210248.64887345580095.3670848262209949.00156377580395.143296688
2209925.24336546580538.484744325
#Sta/Elev= 30
       0 2944.64      29 2939.48    40.3 2935.99      61 2931.85    74.2 2923.84
    85.5 2924.81   103.4 2923.66   108.2 2921.52     144 2897.27   153.4 2892.52
   170.4 2886.51   179.8 2885.05   198.7 2885.98   219.4 2882.35   249.6 2884.39
   284.5  2884.3   324.9 2881.86   339.5 2876.98   351.5 2875.66   363.22877.016
   379.8 2879.28   400.4 2893.82   406.1 2896.29   421.1  2899.1   442.1 2911.03
   471.6  2919.1   482.7 2924.24   511.1 2932.88   539.4 2943.61   569.2 2952.33
#Mann= 3 ,-1,0
       0      .1       0   339.5    .045       0   363.2      .1       0
Bank Sta=339.5,363.2
XS Rating Curve= 0 ,0
Exp/Cntr(USF)=0,0
Exp/Cntr=0.3,0.1

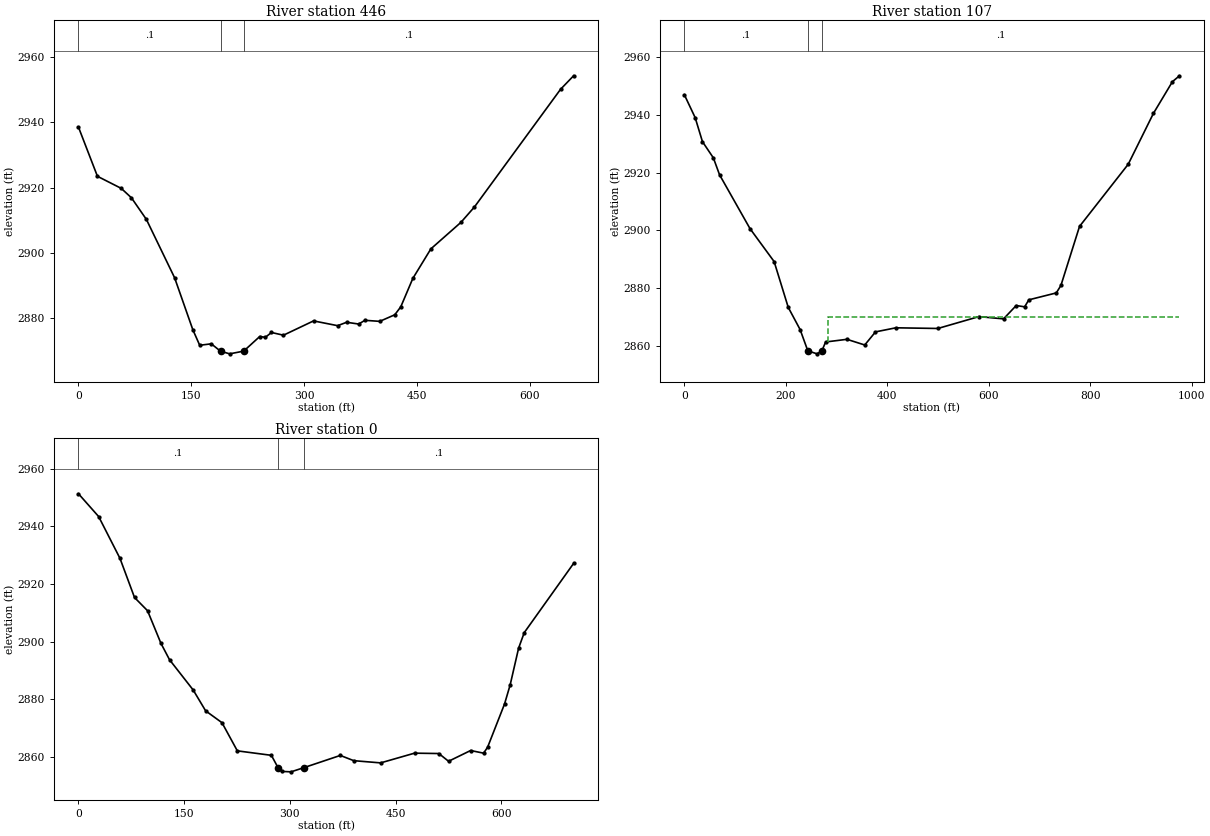
Type RM Length L Ch R = 1 ,446     ,355.4,338.3,330.1
XS GIS Cut Line= 4
2210029.95131076 579985.504573852209953.24689127580103.236938643
2209854.82049697580143.4634323932209859.94737954580555.012647655
#Sta/Elev= 30
       0 2938.49    25.2 2923.47    56.9 2919.77    70.4  2916.9    90.3 2910.29
   127.8 2892.46     152  2876.6   161.2 2871.81   176.6 2872.25   188.92869.992
   201.1 2869.19   219.7 2870.02     241 2874.48   248.6 2874.25   256.6 2875.72
   272.6 2874.89   312.6 2879.26   344.6  2877.8   356.6 2878.84   372.6  2878.3
   380.9 2879.44   400.6 2879.12   420.6 2881.13   428.6 2883.57   444.6 2892.24
   468.6 2901.28   508.6 2909.39   526.5 2914.08     641 2950.05   658.4  2954.2
#Mann= 3 ,-1,0
       0      .1       0   188.9    .045       0   219.7      .1       0
Bank Sta=188.9,219.7
XS Rating Curve= 0 ,0
Exp/Cntr(USF)=0,0
Exp/Cntr=0.3,0.1

Type RM Length L Ch R = 1 ,107     ,95.3,107.2,108.7
XS GIS Cut Line= 4
2209859.91027189579754.3333001522209681.52790099579827.470072221
2209617.80517546580027.8277067762209776.07055757580578.459853705
#Sta/Elev= 30
       0 2946.89    21.3 2938.98    35.7 2930.66    57.2 2925.06    69.4 2919.21
   129.4 2900.61     177 2889.21   204.8 2873.38   228.2 2865.71   243.42858.354
   261.7 2857.32   271.22858.384   278.5 2861.42   320.5 2862.34   355.6 2860.38
   376.8 2864.91   416.9 2866.32   499.8 2866.09   580.6 2870.19   629.2 2869.41
   654.2 2874.02   670.8 2873.57   679.1 2875.99   733.2 2878.38   742.3 2880.95
     779 2901.37     875 2922.86   924.7 2940.45   962.1 2951.39     976 2953.44
#Mann= 3 ,-1,0
       0      .1       0   243.4    .045       0   271.2      .1       0
#XS Ineff= 2 , 0
                          282.65            2870
Permanent Ineff=
       F       F
Bank Sta=243.4,271.2
XS Rating Curve= 0 ,0
Exp/Cntr(USF)=0,0
Exp/Cntr=0.3,0.1

Type RM Length L Ch R = 1 ,0       ,,,
XS GIS Cut Line= 4
2209834.50056629579690.3947807042209631.40429951579775.637117832
2209405.28231693580054.6196838912209282.18275873580058.022378714
#Sta/Elev= 30
       0 2951.33    28.6 2943.42    58.9 2928.87    79.5 2915.29      98 2910.69
     117 2899.36   129.2 2893.66   162.8 2883.13   180.4 2875.91   203.6 2871.79
   225.4    2862   273.7 2860.45  283.192856.135   289.1 2854.85   301.6 2854.71
  319.382856.132   371.5 2860.41   390.6 2858.59   428.7 2857.82   476.8  2861.2
   511.3 2861.07   525.1 2858.38   556.4 2862.12   574.8  2861.2   580.5 2863.27
   604.5 2878.27   612.5 2884.93   624.5 2897.71   632.5 2903.09   702.5 2927.13
#Mann= 3 ,-1,0
       0      .1       0  283.19    .045       0  319.38      .1       0
Bank Sta=283.19,319.38
XS Rating Curve= 0 ,0
Exp/Cntr=0.3,0.1
LCMann Table=0

Chan Stop Cuts=-1
Use User Specified Reach Order=0
Composite Channel Slope=5